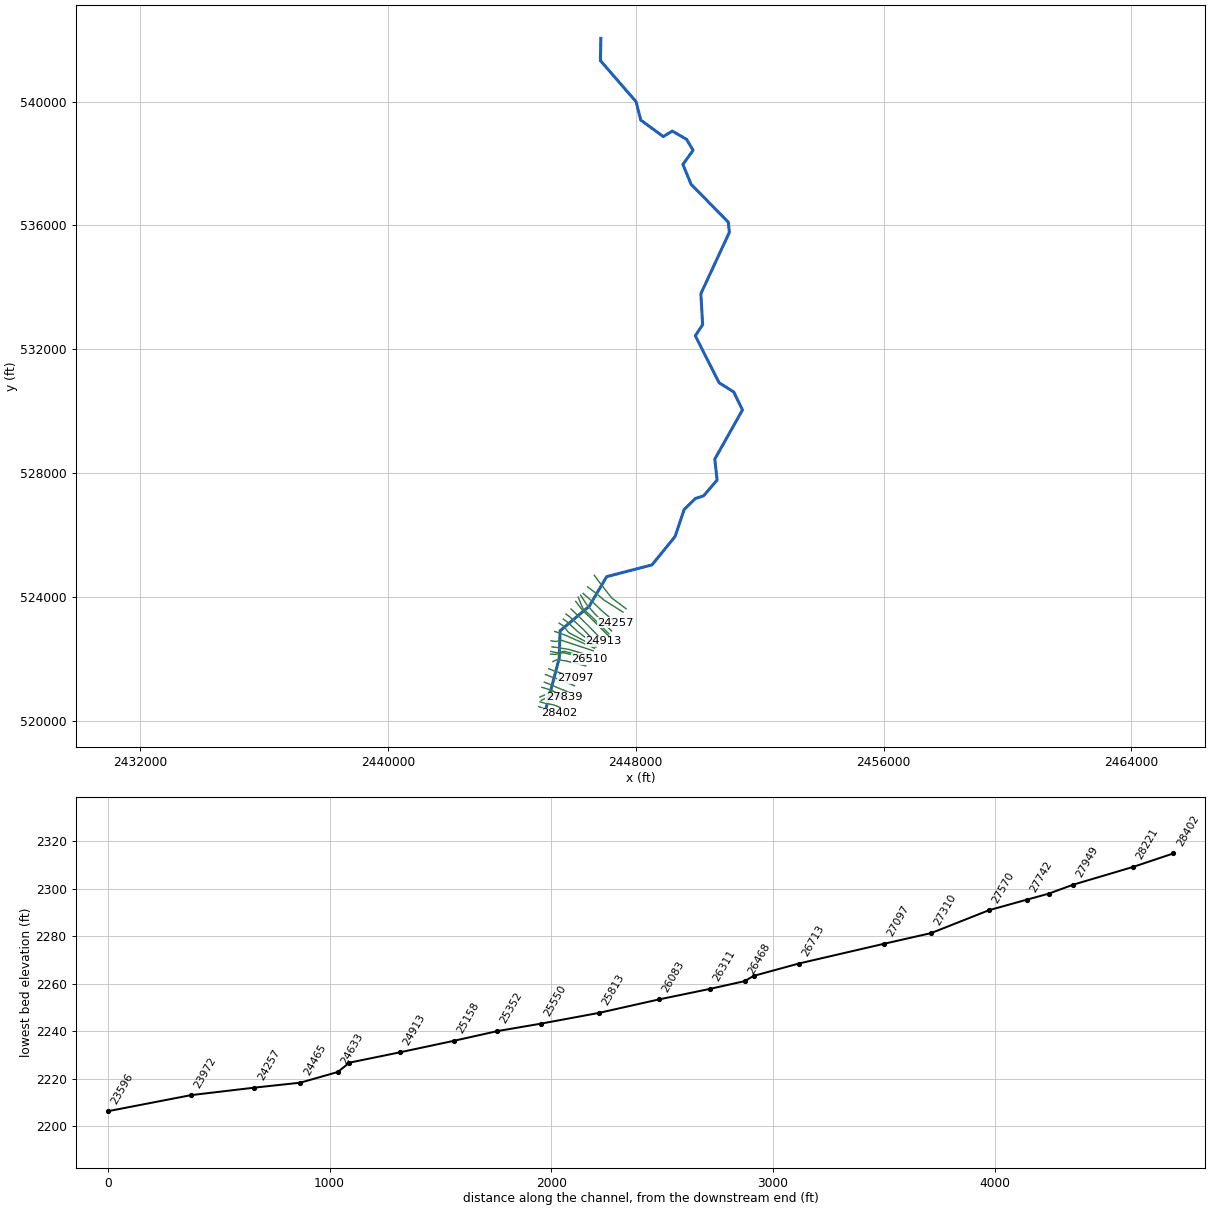
--- BRUSHFK.prj (project) ---

Proj Title=BRUSHFK
Current Plan=p01
Default Exp/Contr=0,0
English Units
Geom File=g01
Flow File=f01
Plan File=p01
Background Map Layer=QC
BEGIN DESCRIPTION:
Stream Name: Brushy Fork
Flood Zone: Zone A
Pendleton County, WV
WVDHSEM Flood Warning & Analysis Mapping
HEC-RAS Version: 5.0.7
Hydrology Method:
Regression was used
Model Notes:
Model ties in with South Fork South Branch South Potomac River
END DESCRIPTION:
DSS File=dss
DSS Export Rating Curves= 0
DSS Export Rating Curve Sorted= 0
DSS Export Volume Flow Curves= 0
DXF OffsetX= 0
DXF OffsetY= 0
DXF ScaleX= 0
DXF ScaleY= 0

--- BRUSHFK.p01 (plan) ---

Plan Title=Floodplain
Program Version=5.07
Short Identifier=Floodplain
Geom File=g01
Flow File=f01
Subcritical Flow
K Sum by GR= 0
Std Step Tol= 0.01
Critical Tol= 0.01
Num of Std Step Trials= 20
Max Error Tol= 0.3
Flow Tol Ratio= 0.001
Split Flow NTrial= 30
Split Flow Tol= 0.02
Split Flow Ratio= 0.02
Log Output Level= 0
Friction Slope Method= 1
Unsteady Friction Slope Method= 2
Unsteady Bridges Friction Slope Method= 1
Parabolic Critical Depth
Global Vel Dist= 0 , 0 , 0
Global Log Level= 0
CheckData=True
Encroach Param=-1 ,0,0, 0
Computation Interval=0.1SEC
Output Interval=1MIN
Instantaneous Interval=Max Profile
Mapping Interval=1HOUR
Computation Time Step Use Courant=        0
Computation Time Step Use Time Series=    0
Computation Time Step Count To Double=0
Computation Time Step Max Doubling=0
Computation Time Step Max Halving=0
Computation Time Step Residence Courant=0
Run HTab= 0
Run UNet= 0
Run Sediment= 0
Run PostProcess= 0
Run WQNet= 0
Run RASMapper= 0
UNET Theta= 0
UNET Theta Warmup= 0
UNET ZTol= 0
UNET ZSATol= 0
UNET MxIter= 0
UNET Max Iter WO Improvement= 0
UNET MaxInSteps= 0
UNET DtIC= 0
UNET DtMin= 0
UNET MaxCRTS= 0
UNET WFStab= 0
UNET SFStab= 0
UNET WFX= 1
UNET SFX= 1
UNET 1D Methodology=Finite Difference
UNET DSS MLevel= 1
UNET Pardiso=0
UNET DZMax Abort= 0
UNET Use Existing IB Tables= 0
UNET Froude Reduction=False
UNET Froude Limit= 0
UNET Froude Power= 0
UNET D1 Cores= 0
UNET D2 Coriolis=0
UNET D2 Cores= 0
UNET D2 Theta= 1
UNET D2 Theta Warmup= 1
UNET D2 Z Tol= 0.01
UNET D2 Volume Tol= 0.01
UNET D2 Max Iterations= 20
UNET D2 Equation= 0
UNET D2 RampUpFraction=0.1
UNET D2 TimeSlices= 1
UNET D2 BCVolumeCheck=0
UNET D1D2 MaxIter= 0
UNET D1D2 ZTol=0.01
UNET D1D2 QTol=0.1
UNET D1D2 MinQTol=1
DSS File=dss
Write IC File= 0
Write IC File at Fixed DateTime=0
Write IC File at Sim End=0
Echo Input=False
Echo Parameters=False
Echo Output=False
Write Detailed= 0
HDF Write Warmup=0
HDF Write Time Slices=0
HDF Flush=0
HDF Face Node Velocities=0
HDF Compression= 1
HDF Chunk Size= 1
HDF Spatial Parts= 1
HDF Use Max Rows=0
HDF Fixed Rows= 1
Calibration Method= 0
Calibration Iterations= 20
Calibration Max Change=0.05
Calibration Tolerance=0.2
Calibration Maximum=1.5
Calibration Minimum=0.5
Calibration Optimization Method= 1
WQ AD Non Conservative
WQ ULTIMATE=-1
WQ Max Comp Step=1HOUR
WQ Output Interval=15MIN
WQ Output Selected Increments= 0
WQ Output face flow=0
WQ Output face velocity=0
WQ Output face area=0
WQ Output face dispersion=0
WQ Output cell volume=0
WQ Output cell surface area=0
WQ Output cell continuity=0
WQ Output cumulative cell continuity=0
WQ Output face conc=0
WQ Output face dconc_dx=0
WQ Output face courant=0
WQ Output face peclet=0
WQ Output face adv mass=0
WQ Output face disp mass=0
WQ Output cell mass=0
WQ Output cell source sink temp=0
WQ Output nsm pathways=0
WQ Output nsm derived pathways=0
WQ Output MaxMinRange=-1
WQ Daily Max Min Mean=-1
WQ Daily Range=0
WQ Daily Time=0
WQ Create Restart=0
WQ Fixed Restart=0
WQ System Summary=0
WQ Write To DSS=0
WQ Use Fixed Temperature=0
Sorting and Armoring Iterations= 10
XS Update Threshold= 0.02
Bed Roughness Predictor= 0
Hydraulics Update Threshold= 0.02
Energy Slope Method= 1
Volume Change Method= 1
Sediment Retention Method= 0
XS Weighting Method= 0
Number of US Weighted Cross Sections= 1
Number of DS Weighted Cross Sections= 1
Upstream XS Weight=0
Main XS Weight=1
Downstream XS Weight=0
Number of DS XS's Weighted with US Boundary= 1
Upstream Boundary Weight= 1
Weight of XSs Associated with US Boundary= 0
Number of US XS's Weighted with DS Boundary= 1
Downstream Boundary Weight= 0.5
Weight of XSs Associated with DS Boundary= 0.5
Percentile Method= 0
Sediment Output Level= 3
Mass or Volume Output= 0
Output Increment Type= 1
Profile and TS Output Increment= 1
XS Output Flag= 0
XS Output Increment= 10
Write Gradation File= 0
Read Gradation Hotstart= 0
Write HDF5 File= 1
Write Binary Output= 1
Write DSS Sediment File= 0
SV Curve= 0
Specific Gage Flag= 0

--- BRUSHFK.f01 (steady flow) ---

Flow Title=Flows
Program Version=5.07
Number of Profiles= 6
Profile Names=P100yr,P10yr,P25yr,P50yr,P500yr,P101yr
River Rch & RM=BRUSHFK,Main            ,28402
     685     319     452     565    1005     833
River Rch & RM=BRUSHFK,Main            ,26083
     872     405     574     719    1283    1061
River Rch & RM=BRUSHFK,Main            ,24257
     980     455     645     807    1444    1193
River Rch & RM=BRUSHFK,Main            ,23596
    1132     524     744     932    1671    1378
River Rch & RM=BRUSHFK,Main            ,20765
    1333     615     875    1097    1970    1622
River Rch & RM=BRUSHFK,Main            ,19682
    1777     817    1164    1461    2635    2162
River Rch & RM=BRUSHFK,Main            ,15210
    2154     988    1409    1770    3202    2622
River Rch & RM=BRUSHFK,Main            ,13214
    2563    1172    1674    2105    3816    3119
River Rch & RM=BRUSHFK,Main            ,5290
    3113    1419    2030    2554    4644    3788
Boundary for River Rch & Prof#=BRUSHFK,Main            , 1
Up Type= 0
Dn Type= 3
Dn Slope=0.01132
Boundary for River Rch & Prof#=BRUSHFK,Main            , 2
Up Type= 0
Dn Type= 3
Dn Slope=0.01132
Boundary for River Rch & Prof#=BRUSHFK,Main            , 3
Up Type= 0
Dn Type= 3
Dn Slope=0.01132
Boundary for River Rch & Prof#=BRUSHFK,Main            , 4
Up Type= 0
Dn Type= 3
Dn Slope=0.01132
Boundary for River Rch & Prof#=BRUSHFK,Main            , 5
Up Type= 0
Dn Type= 3
Dn Slope=0.01132
Boundary for River Rch & Prof#=BRUSHFK,Main            , 6
Up Type= 0
Dn Type= 3
Dn Slope=0.01132
DSS Import GetInterval= 0
DSS Import GetPeak= 0
DSS Import FillOption= 0

--- BRUSHFK.g01 (geometry) ---

Geom Title=Geometry
Program Version=5.07

River Reach=BRUSHFK         ,Main
Reach XY= 30
     2445099.621      520377.078     2445532.734      522025.349
     2445561.562      522910.049     2446501.621      523705.108
     2447064.797      524660.091     2448526.166      525038.851
     2449269.504      525951.796     2449565.947      526828.269
     2449934.658      527188.343     2450189.115      527265.187
     2450628.308      527778.823     2450553.765      528453.645
     2451448.161      530043.322     2451164.543      530624.567
     2450693.044      530921.225     2449925.272      532437.582
     2450161.923      532795.653     2450104.562      533796.165
     2451023.067      535775.859     2450992.599      536102.412
      2449788.54      537332.2392449523.68362874537972.486559704
2449853.87275756538427.7101408412449642.39209212538782.865738801
2449184.82819966539048.191511399     2448891.078      538872.078
      2448163.56      539404.751     2448014.535      539996.251
     2446862.114      541324.099     2446877.035      542043.488

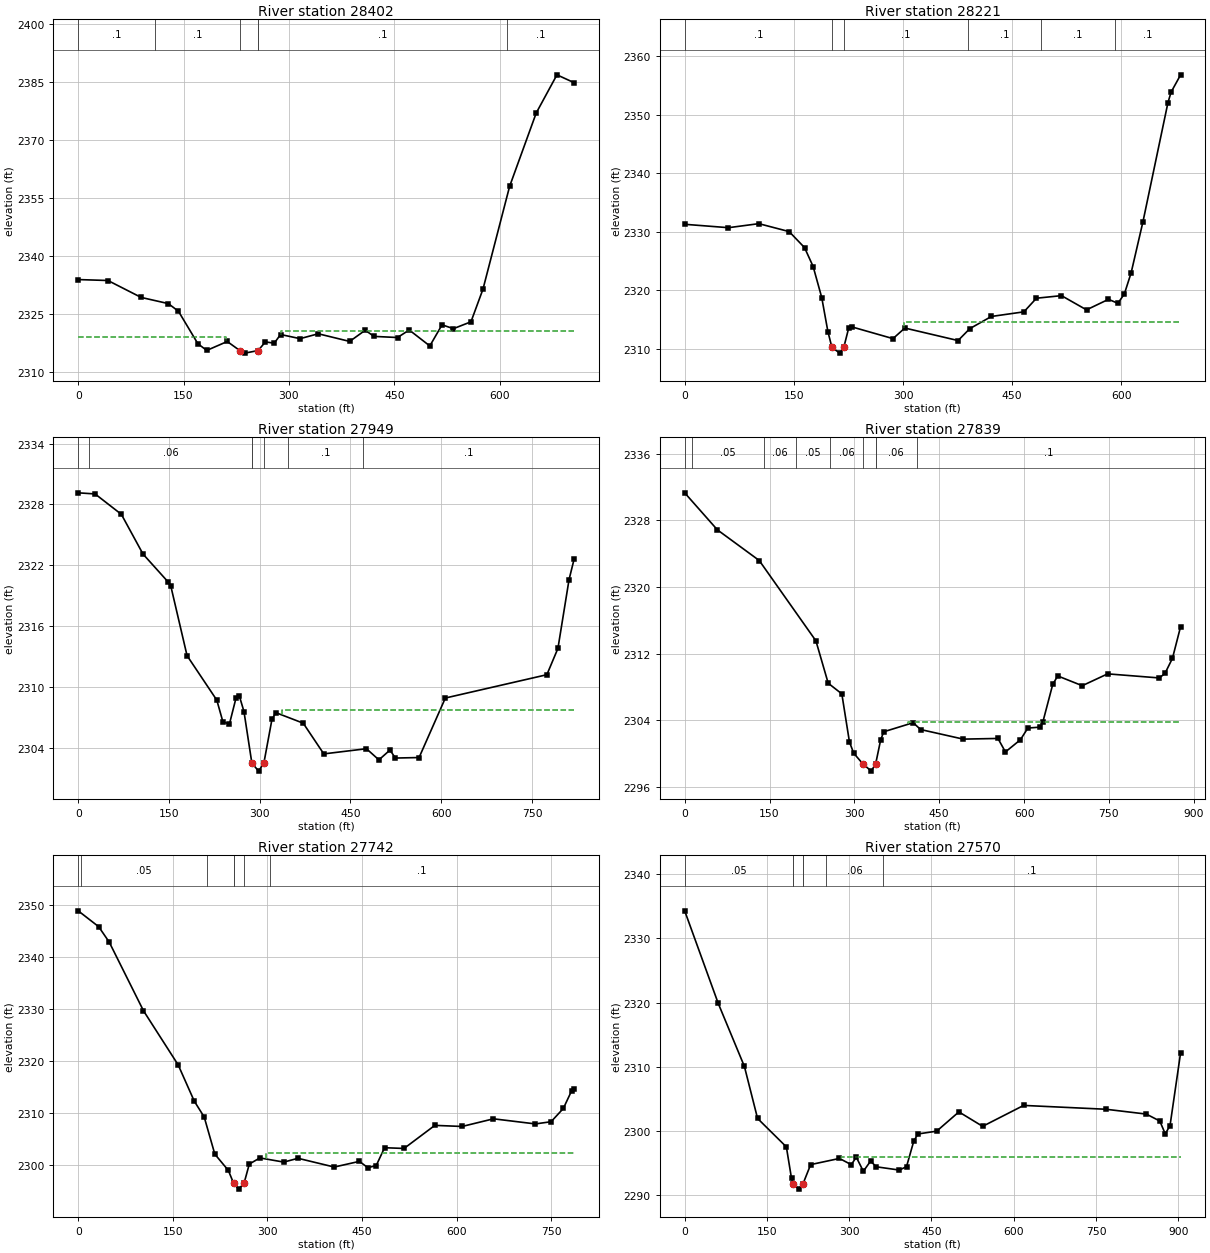
Type RM Length L Ch R = 1 ,28402   ,181.1,181.1,181.1
XS GIS Cut Line= 4
2444871.36834714520464.4024053252445000.96786971520413.275988164
2445358.85278983520305.0782216142445541.95670246520244.439912889
#Sta/Elev= 30
       0 2333.93    42.3 2333.69    89.6 2329.31   128.3 2327.71   142.7 2325.73
   170.4 2317.32     183 2315.59   212.2  2317.9   230.5  2315.5   237.3 2314.89
   256.22315.563   266.5  2317.8   279.1 2317.46   288.1 2319.71   315.9 2318.64
   341.8  2319.9   386.5 2317.92   408.6 2320.81   421.2 2319.22   454.6 2318.93
   471.3 2320.88   500.6 2316.75     518 2322.22   534.2 2321.22   559.2    2323
   576.3 2331.46   614.2 2358.05   652.1 2377.05   681.6 2386.93   706.1 2384.89
#Mann= 6 ,-1 , 0
       0      .1       0  109.01      .1       0   230.5    .045       0
   256.2      .1       0  256.23      .1       0  610.83      .1       0
#XS Ineff= 2 ,-1
       0  209.84 2318.94  288.52706.0859 2320.65
Permanent Ineff=
       F       F
Bank Sta=230.5,256.2
XS Rating Curve= 0 ,0
Exp/Cntr(USF)=0,0
Exp/Cntr=0.3,0.1

Type RM Length L Ch R = 1 ,28221   ,261.4,271.6,287.6
XS GIS Cut Line= 4
2444912.98287273520616.5926703622445066.36212422520571.411185429
2445348.15191182520521.4737547142445566.92541781520434.677744185
#Sta/Elev= 30
       0 2331.25    60.2 2330.67   101.9 2331.36   143.6    2330   164.7 2327.26
   176.5 2324.03   188.3 2318.73   196.8 2312.89   202.32310.199   213.1 2309.22
   218.62310.197   225.3 2313.49   229.3 2313.72   286.2  2311.7   302.5 2313.51
   375.6 2311.37   391.8 2313.41   421.4 2315.49   466.1 2316.28   483.3 2318.61
   517.7 2319.05   552.1 2316.62   582.3 2318.42   595.2 2317.74   604.1 2319.34
   613.4 2322.95   629.6 2331.66     664 2352.06   668.3 2353.85   681.4 2356.81
#Mann= 6 ,-1 , 0
       0      .1       0   202.3    .045       0   218.6      .1       0
  389.03      .1       0  489.37      .1       0  591.07      .1       0
#XS Ineff= 2 , 0
                          301.92         2314.62
Permanent Ineff=
       F       F
Bank Sta=202.3,218.6
XS Rating Curve= 0 ,0
Exp/Cntr(USF)=0,0
Exp/Cntr=0.5,0.3

Type RM Length L Ch R = 1 ,27949   ,107.7,110.3,115.5
XS GIS Cut Line= 4
2444949.84145255520662.9631417412445158.04619013520767.197620138
 2445287.5136031520884.7751686482445666.66816964520723.601450466
#Sta/Elev= 30
       0 2329.15    27.9 2329.04    71.3 2327.03   107.1 2323.11   148.6 2320.36
   153.1 2319.94   179.9 2313.09   229.1  2308.7   239.2 2306.55     250 2306.36
   260.8 2308.91   266.2 2309.14     274 2307.57     2872302.494   298.2  2301.7
   306.92302.509   320.2  2306.8   326.6 2307.47   371.9 2306.43   405.9  2303.4
   476.4 2303.91     497 2302.81   515.3 2303.78   524.2 2302.99   563.4 2303.04
   606.8 2308.91   774.6 2311.21   792.9 2313.81   811.3  2320.6   819.7 2322.63
#Mann= 7 ,-1 , 0
       0      .1       0   17.65     .06       0  286.96     .06       0
     287    .045       0   306.9     .06       0  346.18      .1       0
  470.51      .1       0
#XS Ineff= 2 , 0
             256  2307.7     336          2307.7
Permanent Ineff=
       F       F
Bank Sta=287,306.9
XS Rating Curve= 0 ,0
Exp/Cntr(USF)=0,0
Exp/Cntr=0.5,0.3

Type RM Length L Ch R = 1 ,27839   ,111.4,97.5,74.7
XS GIS Cut Line= 4
2444909.68013261 520771.160908292445146.15632568520872.885304192
2445243.91743343520965.362027739 2445683.8424183520761.913235936
#Sta/Elev= 30
       0 2331.31    57.8 2326.87   131.8 2323.19     232 2313.55   253.7 2308.47
   277.8 2307.19   291.3 2301.41   298.9 2300.06   314.5 2298.83   329.8 2297.92
   337.7 2298.82   346.3 2301.62   351.8 2302.64   403.9 2303.73   417.1 2302.91
   492.4 2301.76   553.8 2301.84     567 2300.22   593.4 2301.68   606.7 2303.09
   628.7  2303.2   633.1  2303.8   650.7 2308.34   659.5 2309.34   702.8 2308.17
   747.7 2309.59     839  2309.1     849 2309.64   862.3 2311.46   876.7 2315.27
#Mann= 9 ,-1 , 0
       0     .06       0   13.18     .05       0  139.64     .06       0
  196.68     .05       0  257.38     .06       0   314.5    .045       0
   337.7     .06       0  337.73     .06       0  410.25      .1       0
#XS Ineff= 1 ,-1
  394.57876.6887 2303.79
Permanent Ineff=
       F
Bank Sta=314.5,337.7
XS Rating Curve= 0 ,0
Exp/Cntr(USF)=0,0
Exp/Cntr=0.5,0.3

Type RM Length L Ch R = 1 ,27742   ,173.3,171.7,171.3
XS GIS Cut Line= 4
2444975.73493514 521085.581768352445136.90865332521036.701214475
2445279.58702679520990.4628527012445702.33776301   520789.656253
#Sta/Elev= 30
       0 2348.85    32.4 2345.81    49.1 2342.86   103.5 2329.66   158.5 2319.27
     184 2312.32   199.8 2309.26   216.6 2302.14     238 2299.02   246.52296.527
   254.4 2295.42     263 2296.55   271.3 2300.24   288.1 2301.41     326 2300.61
   348.5 2301.34     406 2299.66   445.9 2300.75   459.2 2299.54   472.5 2299.94
   485.8 2303.37   516.7 2303.23   565.5 2307.66   608.7 2307.45   658.5 2308.92
   724.9 2307.94   749.8 2308.36   769.2  2310.9   782.4  2314.3   786.4  2314.6
#Mann= 7 ,-1 , 0
       0      .1       0    3.63     .05       0  204.15     .06       0
  246.49     .06       0   246.5    .045       0     263     .06       0
  304.64      .1       0
#XS Ineff= 2 , 0
                          298.47         2302.29
Permanent Ineff=
       F       F
Bank Sta=246.5,263
XS Rating Curve= 0 ,0
Exp/Cntr(USF)=0,0
Exp/Cntr=0.3,0.1

Type RM Length L Ch R = 1 ,27570   ,257.5,260,260
XS GIS Cut Line= 4
2445052.35850608521250.7187746832445205.60564796521195.232740555
2445464.54047389521081.6184801982445888.61230615520907.233801509
#Sta/Elev= 30
       0 2334.31    61.1 2319.91   108.9 2310.07   132.9 2301.97   185.4 2297.54
   194.8 2292.63   197.9 2291.82   207.9 2290.96   215.9 2291.82   229.7 2294.78
   282.2 2295.74   303.8 2294.77   312.9 2295.94   325.8 2293.74     339 2295.33
   349.3 2294.44   391.4 2293.93   404.5 2294.46   417.6  2298.4   425.2 2299.55
   459.5 2299.99     500 2302.99   543.3 2300.74   618.1    2304   768.3  2303.4
   841.7 2302.65   866.3 2301.57   876.3 2299.57     885 2300.86   904.3 2312.22
#Mann= 7 ,-1 , 0
       0     .05       0  197.87     .05       0   197.9    .045       0
   215.9     .05       0  215.92     .05       0   258.2     .06       0
  360.78      .1       0
#XS Ineff= 1 ,-1
  284.34904.2736 2295.97
Permanent Ineff=
       F
Bank Sta=197.9,215.9
XS Rating Curve= 0 ,0
Exp/Cntr(USF)=0,0
Exp/Cntr=0.3,0.1

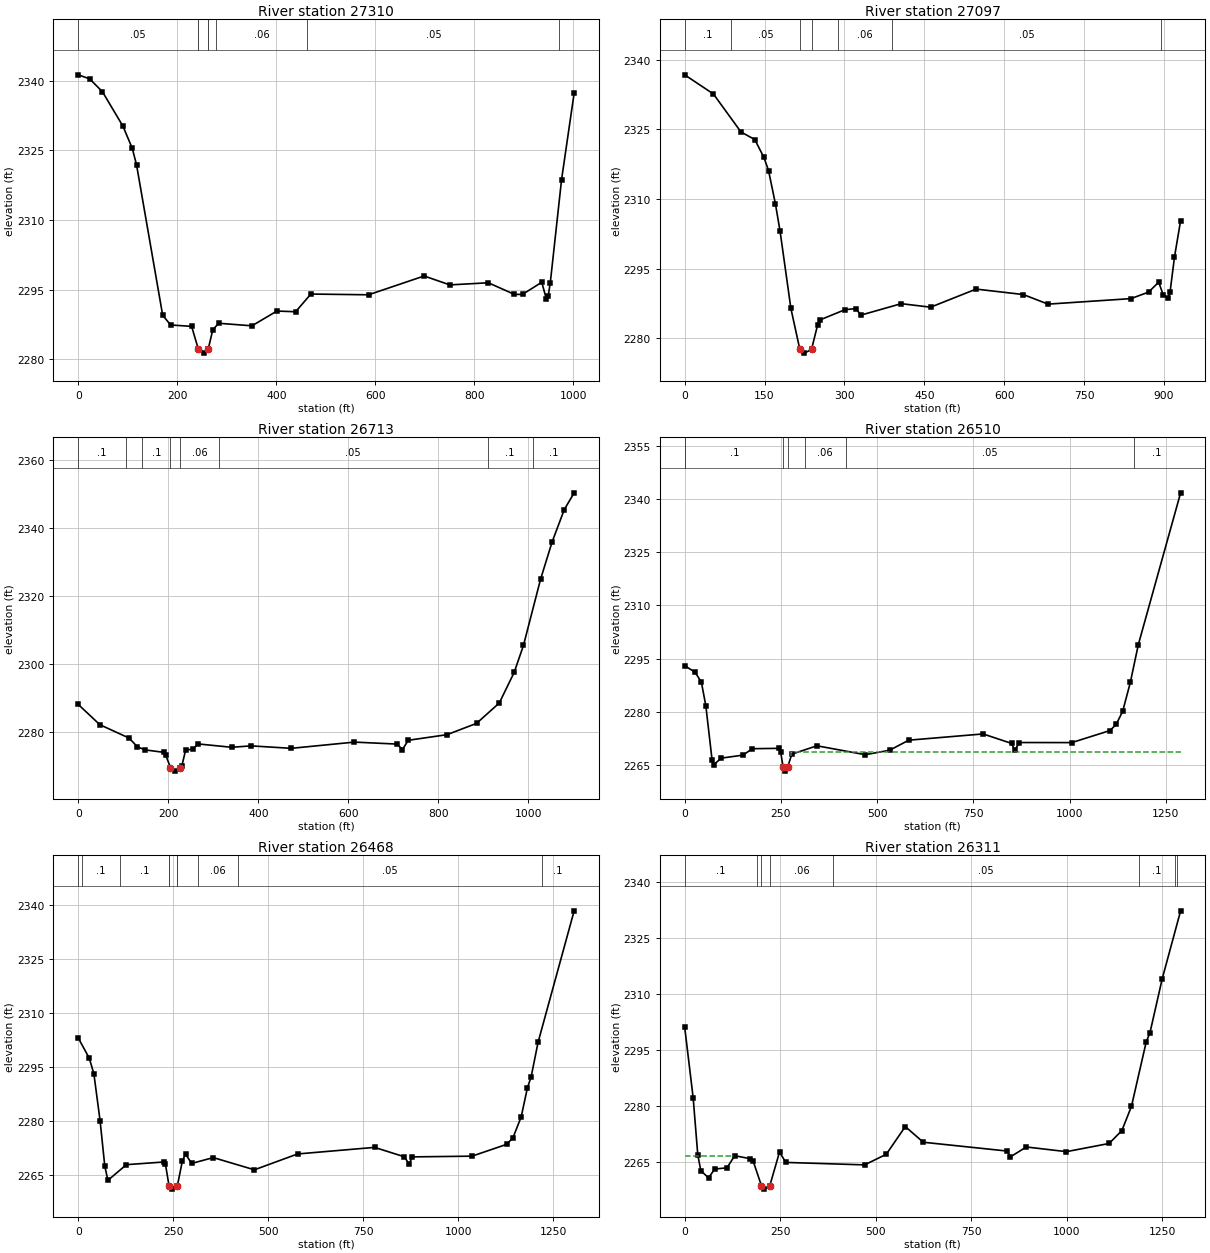
Type RM Length L Ch R = 1 ,27310   ,213,212.7,212.9
XS GIS Cut Line= 4
 2445089.3491955521499.0848322092445278.26593074521423.782357321
2445484.35691465521357.7275547872446023.36410332521138.425610376
#Sta/Elev= 30
       0 2341.26      23  2340.4    48.9 2337.63    90.5 2330.17   109.2 2325.42
   117.8 2321.89   170.6 2289.49   186.7  2287.4   229.1  2287.1   242.3  2282.3
   254.3 2281.34   262.82282.291   271.8 2286.36   283.7 2287.77   350.9 2287.22
   401.3  2290.4   439.1 2290.25   469.9 2294.06   586.4  2293.9   698.7 2297.95
   750.6 2296.03   828.3 2296.49   881.2 2293.98   897.4 2293.99   936.3  2296.6
   945.6 2292.98   949.2 2293.62   953.5 2296.49   976.3 2318.71  1001.7 2337.34
#Mann= 8 ,-1 , 0
       0     .05       0  242.26     .05       0   242.3    .045       0
   262.8     .05       0  262.84     .05       0  279.19     .06       0
  462.56     .05       0  972.07      .1       0
Bank Sta=242.3,262.8
XS Rating Curve= 0 ,0
Exp/Cntr(USF)=0,0
Exp/Cntr=0.3,0.1

Type RM Length L Ch R = 1 ,27097   ,383.3,384.5,388.5
XS GIS Cut Line= 4
2445192.39468745521686.6804714042445358.85278983521620.625668871
2445517.38431591521569.1029228942446069.60246509521374.901803446
#Sta/Elev= 30
       0 2336.76      54 2332.63   105.8 2324.44   131.6 2322.83   148.8 2318.96
   157.5 2316.12   170.4 2308.95   179.1 2303.08   199.4 2286.45   216.22277.636
   224.8 2276.83   238.12277.627   249.4 2282.82   254.7 2284.01     301 2286.19
     322 2286.42   330.4    2285   406.6 2287.48   461.7 2286.72   547.1 2290.62
   635.6 2289.45   682.2 2287.38   837.9 2288.57   870.9 2289.97     890 2292.11
   898.4 2289.37   906.9 2288.66   911.2  2289.9   919.6 2297.54   931.1 2305.37
#Mann= 7 ,-1 , 0
       0      .1       0   86.61     .05       0   216.2    .045       0
   238.1     .05       0  288.71     .06       0  389.38     .05       0
  893.89      .1       0
Bank Sta=216.2,238.1
XS Rating Curve= 0 ,0
Exp/Cntr(USF)=0,0
Exp/Cntr=0.3,0.1

Type RM Length L Ch R = 1 ,26713   ,199,203.1,209.7
XS GIS Cut Line= 4
2445327.14648462 521916.551184222445464.54047389521979.963794653
2445772.35585369521933.7254328792446391.94990146 521776.51500285
#Sta/Elev= 30
       0 2288.14      48 2282.17     113 2278.23   131.7 2275.63   149.2 2274.74
     190 2274.03     194 2273.35     2052269.534   214.2  2268.5   227.22269.538
   230.4 2270.13   238.5 2274.62   254.7 2275.04   266.7  2276.5   340.6 2275.52
   384.1 2275.93   473.3 2275.21   613.6 2277.04   708.5 2276.46   720.3 2274.85
   733.3 2277.58   819.1 2279.22   884.9 2282.55   935.5 2288.56   968.5 2297.54
   989.2 2305.51  1027.1 2324.94  1052.8 2335.95  1079.9 2345.49  1101.8 2350.41
#Mann= 8 ,-1 , 0
       0      .1       0  105.74      .1       0  142.62      .1       0
     205    .045       0   227.2     .06       0  312.18     .05       0
  909.82      .1       0 1009.52      .1       0
Bank Sta=205,227.2
XS Rating Curve= 0 ,0
Exp/Cntr(USF)=0,0
Exp/Cntr=0.5,0.3

Type RM Length L Ch R = 1 ,26510   ,42.6,41.7,41.9
XS GIS Cut Line= 4
2445251.84400973522158.3117614932445401.12786346522147.742993088
2445666.66816964522204.5501232662446509.52744997521999.780235413
#Sta/Elev= 30
       0 2293.03      27  2291.2    43.4 2288.39      55 2281.71    71.1 2266.52
    75.1  2265.1    95.1 2266.98   151.3 2267.83   175.9 2269.64   245.4 2269.74
   249.5 2268.62   255.82264.475   261.8 2263.32   267.62264.472   278.3  2268.1
   343.6 2270.46     469 2267.95   532.4  2269.2   582.2 2272.04   775.3  2273.8
   849.4 2271.13   857.6 2269.18   869.7 2271.38  1005.8 2271.36  1104.9 2274.75
  1121.1 2276.47    1138 2280.17  1157.9 2288.31  1178.7 2298.97  1288.6 2341.75
#Mann= 7 ,-1 , 0
       0      .1       0    2.08      .1       0   255.8    .045       0
   267.6      .1       0  311.69     .06       0  418.28     .05       0
  1166.6      .1       0
#XS Ineff= 2 ,-1
       0     245 2268.65     2771288.583 2268.65
Permanent Ineff=
       F       F
Bank Sta=255.8,267.6
XS Rating Curve= 0 ,0
Exp/Cntr(USF)=0,0
Exp/Cntr=0.5,0.3

Type RM Length L Ch R = 1 ,26468   ,162.9,156.7,152.7
XS GIS Cut Line= 4
2445258.44948998522245.5041008372445452.65060943522203.229027216
2445701.01666696522248.1462929382446526.70169863522032.807636679
#Sta/Elev= 30
       0  2303.1      29 2297.48    41.2 2293.13    57.6 2280.02    69.9 2267.46
    78.1 2263.53   126.8 2267.88   225.3 2268.62   229.3 2268.12     2392261.893
   246.4 2261.08   260.62261.896     274 2268.94   282.2 2270.81   298.4 2268.22
   355.3 2269.84   463.4 2266.45   576.9 2270.85   779.5 2272.68     858 2270.06
   870.4 2267.99   878.7 2270.04  1035.8 2270.24  1126.7 2273.52  1143.3 2275.32
  1165.1 2281.16  1181.5 2289.24  1191.3  2292.3  1209.4 2301.84  1304.4 2338.41
#Mann= 10 ,-1 , 0
       0      .1       0    9.52      .1       0  108.98      .1       0
  238.97      .1       0     239    .045       0   260.6      .1       0
  260.63      .1       0  314.35     .06       0  419.69     .05       0
 1219.45      .1       0
#XS Ineff= 2 , 0
          216.85 2268.34
Permanent Ineff=
       F       F
Bank Sta=239,260.6
XS Rating Curve= 0 ,0
Exp/Cntr(USF)=0,0
Exp/Cntr=0.5,0.3

Type RM Length L Ch R = 1 ,26311   ,221,228,232.5
XS GIS Cut Line= 4
2445300.72456361522390.8246664112445447.36622523522373.650417752
2445831.80517597522312.8799994212446562.37129199522098.862439213
#Sta/Elev= 30
       0 2301.18    22.2 2282.26    34.3 2266.99    42.3 2262.74    62.4 2260.82
    78.6 2263.18   110.8 2263.52   130.9 2266.76   171.3 2265.96   179.4 2265.28
   200.92258.733   207.8 2257.81   222.82258.729   248.3 2267.76   264.5 2264.96
     471  2264.3   527.7 2267.14   577.4 2274.55   624.6 2270.36   844.2    2268
   852.5 2266.44   894.2 2269.09   999.2 2267.84    1111 2270.03  1144.3 2273.48
  1169.5 2279.99  1208.1 2297.24  1217.8 2299.65    1250 2314.14  1298.1  2332.3
#Mann= 8 ,-1 , 0
       0      .1       0  189.82     .06       0   200.9    .045       0
   222.8     .06       0  388.46     .05       0 1188.02      .1       0
 1284.57      .1       0 1288.11      .1       0
#XS Ineff= 2 , 0
          129.79 2266.73
Permanent Ineff=
       F       F
Bank Sta=200.9,222.8
XS Rating Curve= 0 ,0
Exp/Cntr(USF)=0,0
Exp/Cntr=0.3,0.1

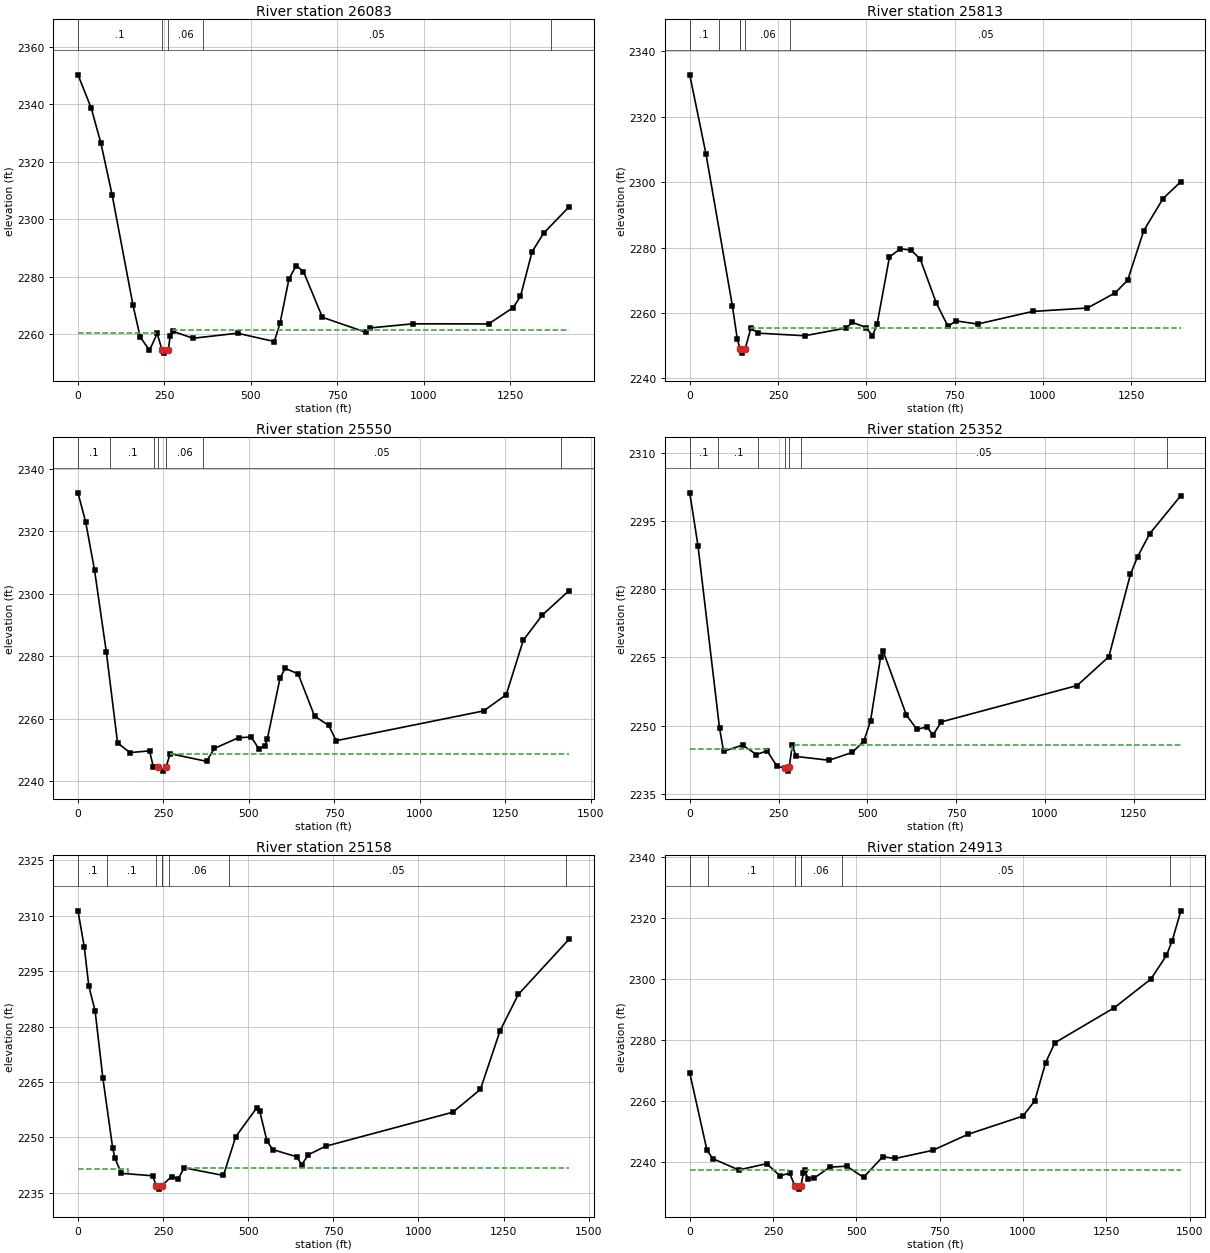
Type RM Length L Ch R = 1 ,26083   ,277.4,270.5,262.2
XS GIS Cut Line= 4
2445272.98154654 522586.346881912445428.87088052522565.209345099
2445599.29227106 522606.163322672446632.38938268522266.641637648
#Sta/Elev= 30
       0 2350.29    38.1 2338.78    66.4 2326.46    98.7 2308.53   159.2 2270.03
   179.8  2259.1   206.7 2254.36   229.2 2260.27   243.2 2254.35   249.7 2253.41
   261.22254.497   266.4  2259.3   274.4 2260.99   332.9 2258.59   461.5 2260.34
   567.8 2257.44   584.6 2264.06   609.9 2279.16     631  2283.9     652  2281.8
   706.7 2265.88   833.1 2260.63   845.7 2262.19   967.8 2263.61  1187.2 2263.57
  1258.3 2269.25  1279.4 2273.15  1313.1 2288.73  1346.7  2295.2    1420 2304.33
#Mann= 5 ,-1 , 0
       0      .1       0   243.2    .045       0   261.2     .06       0
  361.69     .05       0 1367.21      .1       0
#XS Ineff= 2 , 0
          228.83  2260.5  274.96         2261.56
Permanent Ineff=
       F       F
Bank Sta=243.2,261.2
XS Rating Curve= 0 ,0
Exp/Cntr(USF)=0,0
Exp/Cntr=0.3,0.1

Type RM Length L Ch R = 1 ,25813   ,267.9,262.5,254.3
XS GIS Cut Line= 4
2445391.10638038522888.0025834222445469.03111314522862.631740199
2445733.61276389522768.3971796582446672.33396313522349.778266483
#Sta/Elev= 30
       0 2332.81    45.9 2308.63   120.7  2262.2   134.7 2251.98   142.72249.002
   148.8 2247.74   156.92249.028   172.9 2255.32   194.2 2253.84   325.8 2253.06
   442.9 2255.41   460.4 2257.14   499.8 2255.57   517.3 2252.96   530.5 2256.59
   565.5 2277.14   596.2 2279.63   626.8 2279.23   652.6 2276.48     698 2263.09
   731.3  2255.9   753.8 2257.59   815.2 2256.63   970.6 2260.48  1126.1 2261.53
    1205 2266.19    1240 2270.05  1285.6 2285.19  1340.1 2294.99  1390.6 2300.15
#Mann= 6 ,-1 , 0
       0      .1       0   81.91     .06       0  142.66     .06       0
   142.7    .045       0   156.9     .06       0  283.64     .05       0
#XS Ineff= 2 , 0
                          172.53         2255.45
Permanent Ineff=
       F       F
Bank Sta=142.7,156.9
XS Rating Curve= 0 ,0
Exp/Cntr(USF)=0,0
Exp/Cntr=0.3,0.1

Type RM Length L Ch R = 1 ,25550   ,196.5,197.7,199.7
XS GIS Cut Line= 4
2445530.64601811523158.0208434352445681.05887436523056.537470544
2445840.53274604522851.7585216752446721.26344649522386.022328229
#Sta/Elev= 30
       0 2332.34    22.5 2323.01    48.4 2307.65      83 2281.32   115.9 2252.24
   152.2 2249.12   209.5 2249.68   220.9 2244.37   235.1 2244.45   249.4 2243.19
   257.9 2244.55   269.7 2248.78   376.2 2246.33     399 2250.44   469.9 2253.91
   506.8 2254.09   529.1 2250.42   546.9 2251.27   554.1 2253.43   591.3 2272.93
   606.4 2276.14   644.5 2274.31   692.4 2260.81   733.8 2257.85   755.7 2252.94
  1187.3 2262.48  1253.4 2267.67  1303.2  2285.1  1358.4 2293.11  1437.3 2301.03
#Mann= 7 ,-1 , 0
       0      .1       0   94.21      .1       0   223.9     .06       0
   235.1    .045       0   257.9     .06       0   366.2     .05       0
  1414.6      .1       0
#XS Ineff= 1 ,-1
  269.611437.288 2248.79
Permanent Ineff=
       F
Bank Sta=235.1,257.9
XS Rating Curve= 0 ,0
Exp/Cntr(USF)=0,0
Exp/Cntr=0.3,0.1

Type RM Length L Ch R = 1 ,25352   ,198,194.5,195.9
XS GIS Cut Line= 4
2445668.37345275523290.3116688112445815.16190282523176.142874308
2446125.04863075522889.8147865092446739.38547736522416.829780714
#Sta/Elev= 30
       0 2301.17    23.3 2289.48    83.9 2249.45    95.3 2244.38   148.9 2245.75
   187.8 2243.67   217.7 2244.48     246 2241.08   267.1 2240.74   276.2 2240.03
     280 2240.93   288.9 2245.69   299.8 2243.25   392.3 2242.42   457.7 2244.14
   490.4 2246.62   509.2 2251.07   537.6 2265.16   544.8 2266.38     610 2252.37
   639.7 2249.21   668.2 2249.74   685.3 2247.96   708.1 2250.84  1091.3 2258.84
  1180.5 2265.19    1241 2283.23  1261.2 2287.11  1295.7 2292.22  1383.2 2300.56
#Mann= 7 ,-1 , 0
       0      .1       0   79.85      .1       0  193.41     .06       0
   267.1    .045       0     280     .06       0  312.55     .05       0
 1344.04      .1       0
#XS Ineff= 2 ,-1
       0  217.29 2244.94  286.741383.199 2245.71
Permanent Ineff=
       F       F
Bank Sta=267.1,280
XS Rating Curve= 0 ,0
Exp/Cntr(USF)=0,0
Exp/Cntr=0.3,0.1

Type RM Length L Ch R = 1 ,25158   ,246.6,244.6,247
XS GIS Cut Line= 4
2445755.35920094523449.7855404962445865.90358927523368.236401566
2446300.83233023522965.9273161772446795.56377307522453.073842461
#Sta/Elev= 30
       0 2311.36    18.4 2301.62    31.8 2291.01    50.3 2284.24    73.1 2266.07
   101.7 2247.24   108.6 2244.32   127.5 2240.25   220.2 2239.58   229.12236.898
   236.6 2235.97   246.3 2236.89   274.8 2239.38   294.6 2238.73   311.6 2241.75
   427.3 2239.67   463.3 2250.17   525.4 2258.03     534 2257.03     555 2249.03
     572 2246.67   642.8 2244.74   656.9 2242.55   676.7 2245.29     727 2247.58
  1101.1 2256.81    1182 2262.99  1239.7 2278.88  1293.5 2288.73  1442.4 2303.68
#Mann= 8 ,-1 , 0
       0      .1       0   84.19      .1       0   229.1    .045       0
   246.3      .1       0  246.33      .1       0  267.93     .06       0
  442.61     .05       0  1432.4      .1       0
#XS Ineff= 2 , 0
          147.43 2241.48  317.47         2241.73
Permanent Ineff=
       F       F
Bank Sta=229.1,246.3
XS Rating Curve= 0 ,0
Exp/Cntr(USF)=0,0
Exp/Cntr=0.3,0.1

Type RM Length L Ch R = 1 ,24913   ,227,227,227.4
XS GIS Cut Line= 4
2445916.64527571523614.6960214442446094.24117827523444.348931235
2446501.98687292523043.8520489332446956.84984784522570.867043138
#Sta/Elev= 30
       0 2269.23    51.7 2243.85    69.2  2241.1     147 2237.39   230.9 2239.45
     271 2235.44   299.5 2236.37     3152232.289   326.7  2231.1   333.8 2232.27
   340.8  2236.3   345.2 2237.27     355 2234.55   371.9 2234.64   420.6 2238.31
   470.9 2238.63   521.5 2234.97   579.2 2241.71   616.8 2241.16     729 2243.82
   835.8 2249.12   999.9 2255.07  1035.4 2260.08  1067.8 2272.55  1095.7 2279.12
  1274.3 2290.63  1384.2 2300.05  1430.4 2307.75  1447.7 2312.54  1473.8  2322.4
#Mann= 7 ,-1 , 0
       0      .1       0   55.21      .1       0     315    .045       0
   333.8     .06       0  333.84     .06       0  455.47     .05       0
 1441.54      .1       0
#XS Ineff= 2 , 0
          295.76 2237.34   344.6         2237.49
Permanent Ineff=
       F       F
Bank Sta=315,333.8
XS Rating Curve= 0 ,0
Exp/Cntr(USF)=0,0
Exp/Cntr=0.5,0.3

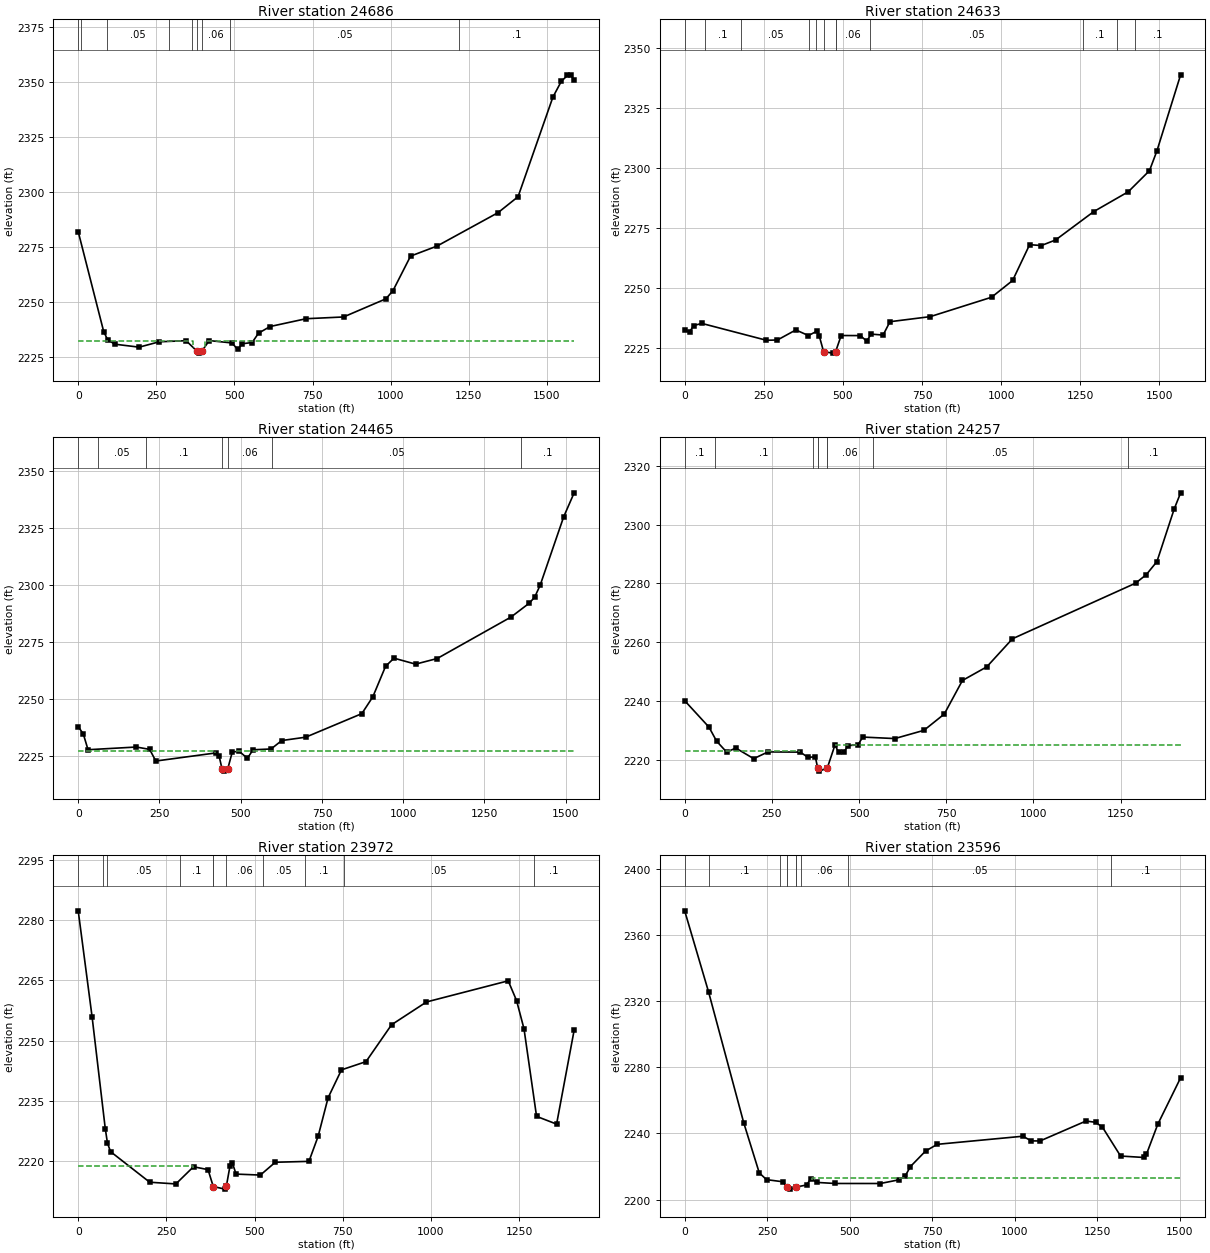
Type RM Length L Ch R = 1 ,24686   ,52.4,53.2,54.9
XS GIS Cut Line= 4
2446065.24592887523861.1556413222446280.89809627523578.451959698
2446541.85534084523326.5557305582447158.00439054522714.031087037
#Sta/Elev= 30
       0  2281.9    81.6 2236.51      94 2232.87   116.8 2230.82     195 2229.47
   259.4 2231.91   345.4 2232.41   378.92227.784   385.9 2226.76   396.3 2227.78
   419.3 2232.46   492.3 2231.38   510.4 2228.41   524.9 2231.02   556.5 2231.57
   577.2 2235.84   614.1 2238.84   729.1 2242.38   849.2 2243.18   984.6 2251.41
  1007.2 2255.09  1063.6 2270.81  1148.2 2275.36  1343.7 2290.55  1407.6 2297.78
  1519.1    2343  1546.1 2350.18  1565.6 2352.82  1575.7 2353.11  1587.1 2350.77
#Mann= 9 ,-1 , 0
       0      .1       0    7.83      .1       0   93.17     .05       0
  289.46      .1       0  365.49     .06       0   378.9    .045       0
   396.3     .06       0  486.41     .05       0 1217.05      .1       0
#XS Ineff= 2 ,-1
       0     368 2232.39     4061587.072 2232.39
Permanent Ineff=
       F       F
Bank Sta=378.9,396.3
XS Rating Curve= 0 ,0
Exp/Cntr(USF)=0,0
Exp/Cntr=0.5,0.3

Type RM Length L Ch R = 1 ,24633   ,173.1,168.4,166.5
XS GIS Cut Line= 4
2446144.98286472523997.0708728722446297.20792405523634.630255405
2446692.26819709523259.5042163262447136.25795349522813.702256841
#Sta/Elev= 30
       0 2232.45    15.4 2231.61    28.4 2234.32    54.4 2235.19   258.3 2228.17
     293 2228.28   351.3 2232.48     391 2230.13   417.3 2231.93   425.1 2230.04
     4392223.413   467.6 2222.81   476.82223.388   494.5 2230.15   555.3 2230.12
   575.1  2227.8   589.2 2230.74   626.9 2230.34   648.7 2235.91   775.8 2238.02
   969.7 2246.11  1036.2 2253.09    1090 2268.03  1126.8 2267.66    1172 2269.98
  1292.8 2281.83  1401.7 2290.08  1468.6 2298.86    1492 2307.03  1567.1 2338.83
#Mann= 12 ,-1 , 0
       0      .1       0   63.92      .1       0  178.44     .05       0
  394.37      .1       0   414.6     .06       0     439    .045       0
   476.8     .06       0  476.85     .06       0  585.96     .05       0
  1258.6      .1       0 1364.54     .05       0 1423.38      .1       0
Bank Sta=439,476.8
XS Rating Curve= 0 ,0
Exp/Cntr(USF)=0,0
Exp/Cntr=0.5,0.3

Type RM Length L Ch R = 1 ,24465   ,205.9,207.4,206.3
XS GIS Cut Line= 4
2446224.71980056524058.6857778422446427.68654634523748.799049907
2446686.83158783523453.4099466712447219.61929551522907.936817382
#Sta/Elev= 30
       0 2237.86    15.8 2234.54    30.2  2227.7   178.9 2228.88   219.7 2227.85
   238.8 2222.75     425 2226.32   433.5 2224.93   442.42219.358   447.9 2218.32
   460.22219.369   474.1 2226.76   495.8 2226.93   520.6 2223.95   537.9 2227.67
   593.4 2228.03   626.2 2231.72   699.9 2233.19   872.6 2243.51   906.4 2250.86
   945.8 2264.29   971.6 2267.81    1038  2265.2  1104.5 2267.66  1331.7 2285.84
  1387.6 2291.89  1404.4 2294.53  1421.4 2299.81  1493.8  2329.8  1525.9 2340.26
#Mann= 7 ,-1 , 0
       0      .1       0      61     .05       0  208.19      .1       0
   442.4    .045       0   460.2     .06       0  596.56     .05       0
 1361.85      .1       0
#XS Ineff= 2 ,-1
       0  422.39 2226.93  488.411525.889 2227.34
Permanent Ineff=
       F       F
Bank Sta=442.4,460.2
XS Rating Curve= 0 ,0
Exp/Cntr(USF)=0,0
Exp/Cntr=0.3,0.1

Type RM Length L Ch R = 1 ,24257   ,285.6,285.7,286.5
XS GIS Cut Line= 4
2446302.64453331524120.3006828112446558.16516863523893.775296894
 2446906.1081614523560.3299288242447360.97113632523170.706265046
#Sta/Elev= 30
       0 2240.16    69.6 2231.19    91.7 2226.39   120.1 2222.73   146.8 2224.05
   197.9 2220.47   239.1 2222.76   331.6 2222.69   353.4 2220.91   374.5 2221.09
   381.62217.293   386.4 2216.23     409 2217.29   430.9 2225.07     442 2222.56
   455.5 2222.64   469.7 2224.93   496.7 2225.12   510.8  2227.8   602.7 2227.29
   686.2 2230.09   744.5 2235.62   796.6 2247.03   866.4 2251.66   940.1  2261.2
    1293 2280.07  1323.7 2282.95  1354.4 2287.42  1403.6 2305.19  1422.3 2310.77
#Mann= 9 ,-1 , 0
       0      .1       0    86.9      .1       0  369.02     .06       0
  381.59     .06       0   381.6    .045       0     409     .06       0
  409.02     .06       0  539.26     .05       0 1269.97      .1       0
#XS Ineff= 2 , 0
          328.32 2223.22  430.53         2225.03
Permanent Ineff=
       F       F
Bank Sta=381.6,409
XS Rating Curve= 0 ,0
Exp/Cntr(USF)=0,0
Exp/Cntr=0.3,0.1

Type RM Length L Ch R = 1 ,23972   ,377.1,375.4,375.2
XS GIS Cut Line= 4
2446449.43298339524328.7040378552446726.70005575524120.300682811
2446974.97187872523904.648515418 2447592.9331315523515.024851641
#Sta/Elev= 30
       0 2282.33    39.4 2255.91    76.7 2228.14    82.9 2224.53    91.7  2222.4
   202.7 2214.79   276.9 2214.36   326.9 2218.64   368.1 2217.92   382.9 2213.72
   415.9 2213.07   419.92213.727   430.1 2218.71     437 2219.62   447.6 2216.81
   516.5 2216.57   558.8 2219.76   654.2 2219.98   680.2  2226.2   708.5  2235.8
   746.4 2242.75     816  2244.8   888.5 2253.98   987.5 2259.65  1219.2 2264.91
  1242.9    2260    1264 2252.97  1299.6 2231.18  1356.4 2229.25  1406.2 2252.64
#Mann= 11 ,-1 , 0
       0      .1       0   69.13      .1       0   82.31     .05       0
  289.36      .1       0  382.85      .1       0   382.9    .045       0
   419.9     .06       0  524.96     .05       0  641.78      .1       0
  752.28     .05       0 1291.83      .1       0
#XS Ineff= 2 , 0
           324.7 2218.74  431.43         2216.83
Permanent Ineff=
       F       F
Bank Sta=382.9,419.9
XS Rating Curve= 0 ,0
Exp/Cntr(USF)=0,0
Exp/Cntr=0.3,0.1

Type RM Length L Ch R = 1 ,23596   ,267.1,267.9,263.2
XS GIS Cut Line= 4
2446666.89735387524703.8300769342446788.31496072524533.482986724
2447226.86810786 523971.70002965 2447692.6043013523623.757036881
#Sta/Elev= 30
       0 2374.57    72.3 2325.61   178.9 2246.47   226.1 2216.13     248 2212.03
   298.7 2210.71   308.82207.472   318.2 2206.29   335.92207.472   369.5  2208.8
   382.1  2212.5   401.7 2210.34     455 2209.71   593.1 2209.69   648.7  2211.9
   668.2 2214.18   684.4 2219.97   730.1 2229.31   765.6 2233.38  1025.3 2238.28
  1050.2 2235.46    1077 2235.41  1216.3 2247.46  1245.3 2246.71  1266.2 2243.77
  1321.2  2226.3  1391.1 2225.44  1399.6 2227.36  1433.9 2245.48  1503.2 2273.61
#Mann= 10 ,-1 , 0
       0      .1       0   73.69      .1       0  287.46     .05       0
  308.79     .05       0   308.8    .045       0   335.9     .05       0
  335.94     .05       0  352.49     .06       0  494.97     .05       0
 1293.13      .1       0
#XS Ineff= 2 , 0
                          386.21         2212.89
Permanent Ineff=
       F       F
Bank Sta=308.8,335.9
XS Rating Curve= 0 ,0
Exp/Cntr(USF)=0,0
Exp/Cntr=0.5,0.3