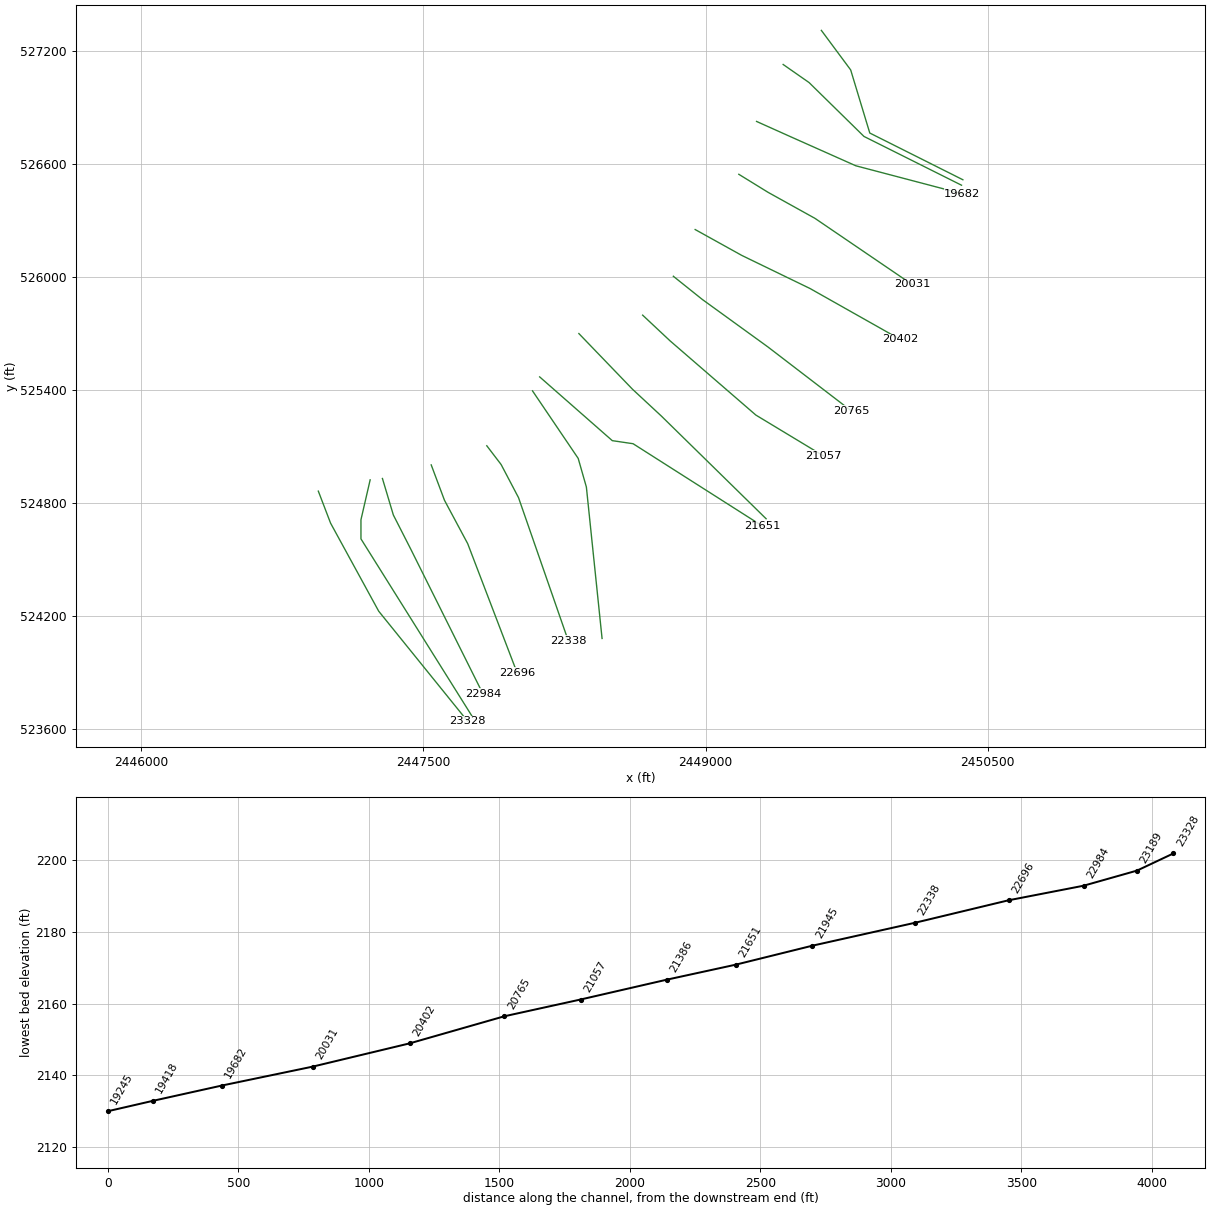
HEC-RAS study BRUSHFK.prj: BRUSHFK

--- BRUSHFK.g01 (geometry) --- (continued)

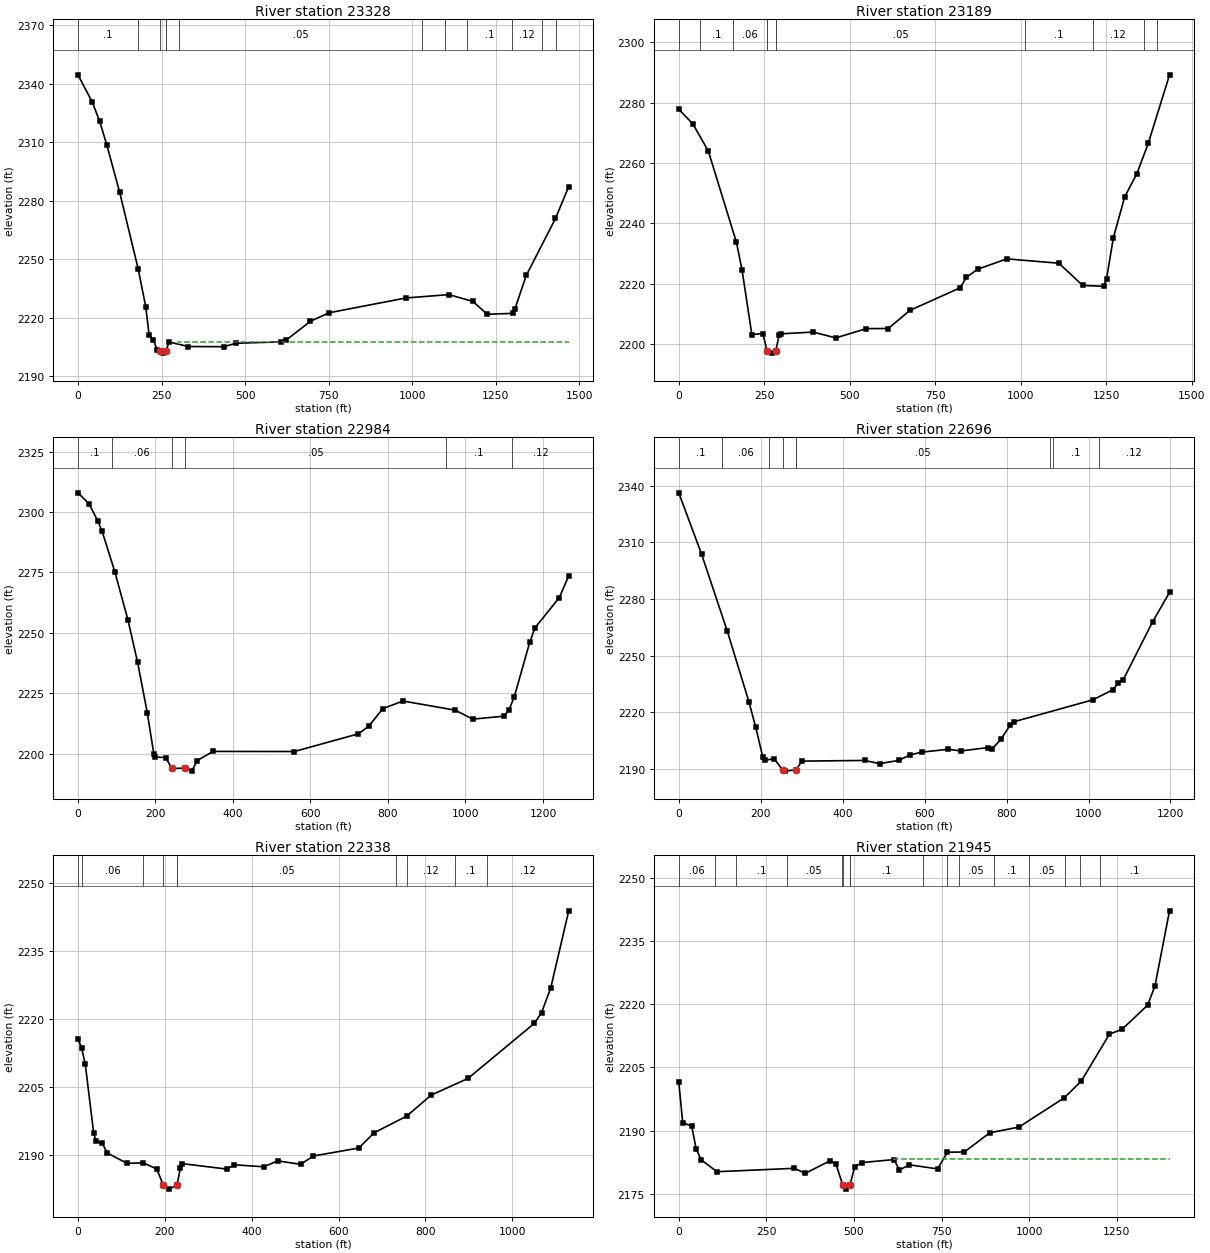
Type RM Length L Ch R = 1 ,23328   ,144.2,139.7,128.6
XS GIS Cut Line= 4
2446942.35222314 524863.303948622447007.59153429 524692.95685841
 2447263.1121696524225.408461877 2447736.0971754523640.066864667
#Sta/Elev= 30
       0 2344.46    43.3 2330.32    64.7 2320.73    86.1 2308.67   124.7 2284.27
   180.5 2244.73     203  2225.3   212.8 2211.13   225.8 2208.72   236.4 2203.51
     244 2202.71   254.1 2201.82   262.82202.687   272.4 2207.52   330.6 2205.19
   436.8 2205.13   472.6 2206.88     606 2207.59   622.5 2208.44   695.3 2218.15
   750.9 2222.49   980.7 2230.09  1109.3 2231.81  1181.3 2228.31  1223.8 2221.74
  1299.8  2222.2  1306.5  2224.3  1340.7 2241.62  1428.2 2270.84  1467.8 2287.15
#Mann= 12 ,-1 , 0
       0      .1       0  178.67     .06       0     244    .045       0
   262.8     .06       0  262.84     .06       0  301.22     .05       0
 1030.24      .1       0 1097.05     .05       0 1163.57      .1       0
 1296.91     .12       0 1387.25      .1       0 1430.24     .12       0
#XS Ineff= 2 ,-1
       0  201.35 2207.43  299.361467.783  2207.5
Permanent Ineff=
       F       F
Bank Sta=244,262.8
XS Rating Curve= 0 ,0
Exp/Cntr(USF)=0,0
Exp/Cntr=0.5,0.3

Type RM Length L Ch R = 1 ,23189   ,191,204.6,210.8
XS GIS Cut Line= 4
2447217.80709242524923.1066505022447168.87760906524711.078889283
2447168.87760906524609.5955163922447761.46801862523663.625504802
#Sta/Elev= 30
       0 2277.78    41.3 2272.92    86.4 2263.97   168.5  2233.8     185 2224.65
   213.7 2203.18   245.8 2203.49   258.72197.638   273.8 2197.03   283.42197.638
   293.8 2203.17   297.8 2203.42   393.1    2204   459.2 2202.07   548.6 2205.15
   612.6 2205.18   676.3  2211.2   822.6 2218.65   841.5 2222.17   874.5 2224.84
   959.5 2228.24  1111.8  2226.8  1181.3 2219.45  1242.7 2219.15  1251.1 2221.65
    1271 2235.22    1304 2248.73  1339.8 2256.48    1373 2266.46  1435.3 2289.19
#Mann= 11 ,-1 , 0
       0      .1       0   61.55      .1       0  159.33     .06       0
  258.66     .06       0   258.7    .045       0   283.4     .05       0
  283.42     .05       0 1012.64      .1       0 1210.14     .12       0
 1360.69      .1       0 1399.68     .12       0
Bank Sta=258.7,283.4
XS Rating Curve= 0 ,0
Exp/Cntr(USF)=0,0
Exp/Cntr=0.5,0.3

Type RM Length L Ch R = 1 ,22984   ,287.9,287.6,288.7
XS GIS Cut Line= 4
2447283.04640356524930.3554628512447341.03690236524736.449732506
2447433.45925981524555.2294237722447817.64631433523785.043111654
#Sta/Elev= 30
       0 2307.93    28.7 2303.37    50.7 2296.45    62.1 2292.15      95 2275.36
   128.9 2255.41   153.9 2237.87     179 2216.86   195.7 2200.01   199.8 2198.65
   226.6 2198.43   242.12193.923   276.2 2194.04   293.9 2192.82   307.4 2197.17
   348.7 2200.97   558.2 2200.93   723.6 2208.24     750 2211.33   787.2 2218.71
   838.8 2221.82   973.7 2218.03  1018.4 2214.33  1099.1 2215.54  1112.5 2218.22
  1125.8 2223.46  1166.1 2246.25  1179.5 2252.11  1242.1 2264.59  1266.5 2273.58
#Mann= 6 ,-1 , 0
       0      .1       0   87.03     .06       0   242.1    .045       0
   276.2     .05       0  950.37      .1       0 1120.48     .12       0
Bank Sta=242.1,276.2
XS Rating Curve= 0 ,0
Exp/Cntr(USF)=0,0
Exp/Cntr=0.3,0.1

Type RM Length L Ch R = 1 ,22696   ,358.5,358.8,358.3
XS GIS Cut Line= 4
2447542.19144505525002.8435863452447612.86736546524814.374465261
 2447736.0971754 524584.224673172447998.86662306523897.399703069
#Sta/Elev= 30
       0 2336.29    55.5  2303.9   118.5 2262.93   171.3 2225.47   187.9 2211.95
   205.2  2196.1   209.8 2194.42   232.5  2195.4   253.22189.468   259.7 2188.76
   286.32189.465   300.5 2194.07   453.5 2194.42   490.2 2192.73   536.6 2194.43
   564.6 2197.35   592.9 2198.83   657.5 2200.33   688.5 2199.45   753.5 2201.21
   763.6 2200.23   787.6 2206.01   809.3 2213.37   819.2 2215.01  1010.6 2226.55
  1060.2 2231.98  1071.9 2235.39  1084.8 2237.22  1156.2 2267.84  1197.7  2283.5
#Mann= 9 ,-1 , 0
       0      .1       0  106.09     .06       0  219.54     .05       0
   253.2    .045       0   286.3     .05       0  286.32     .05       0
  905.34     .12       0  913.03      .1       0 1025.37     .12       0
Bank Sta=253.2,286.3
XS Rating Curve= 0 ,0
Exp/Cntr(USF)=0,0
Exp/Cntr=0.3,0.1

Type RM Length L Ch R = 1 ,22338   ,399,392.3,389.2
XS GIS Cut Line= 4
2447837.58054829525104.3269592362447913.69307796525004.655789432
2448006.11543541 524828.872089962448270.69708616524067.746793278
#Sta/Elev= 30
       0 2215.67     8.5 2213.59    16.9    2210    36.1 2194.93    41.5 2193.03
    56.1 2192.56    67.8 2190.43   113.2 2188.17     150  2188.3   181.6 2186.93
   196.12183.427   210.4 2182.49   228.12183.411   235.9 2187.22   240.4 2188.11
     343 2186.91     360 2187.86   427.7 2187.42   459.9 2188.73   512.4 2187.96
   542.1  2189.8   646.6 2191.56   681.8 2194.93   756.6 2198.58     813 2203.22
   897.8  2206.9  1050.3 2219.03  1067.2 2221.42  1088.4 2226.88  1129.8 2243.88
#Mann= 10 ,-1 , 0
       0      .1       0    9.53     .06       0  150.62     .05       0
   196.1    .045       0   228.1     .05       0  228.15     .05       0
  731.62      .1       0  756.45     .12       0   866.9      .1       0
  940.57     .12       0
Bank Sta=196.1,228.1
XS Rating Curve= 0 ,0
Exp/Cntr(USF)=0,0
Exp/Cntr=0.3,0.1

Type RM Length L Ch R = 1 ,21945   ,269.6,293.8,307.8
XS GIS Cut Line= 4
2448080.41576199525396.091656297 2448323.2509757525037.275445004
2448366.74384979524885.0503856682448450.10519181 524080.43221489
#Sta/Elev= 30
       0 2201.57    11.3 2191.86    37.1 2191.08    49.7  2185.6    64.2 2183.06
   109.1 2180.25   329.9 2181.06     361 2179.87   431.7 2182.84   448.2 2182.16
   468.12177.057   477.3 2176.12   488.32177.057   502.3 2181.46   523.1 2182.42
   613.9 2183.13   629.9 2180.66   658.1 2181.89   738.5 2180.92   766.7 2184.88
   814.9 2184.93   887.3 2189.48   970.8 2190.84    1100 2197.78  1148.7 2201.75
  1229.1 2212.89  1265.3 2214.05  1337.7 2219.74  1358.8 2224.27  1400.5 2242.14
#Mann= 16 ,-1 , 0
       0     .06       0  103.79      .1       0  163.12      .1       0
  307.94     .05       0  464.71      .1       0   468.1    .045       0
   488.3      .1       0  488.31      .1       0  697.67     .05       0
  765.52      .1       0  798.51     .05       0  899.36      .1       0
  1000.2     .05       0 1101.05      .1       0 1146.14     .12       0
 1201.89      .1       0
#XS Ineff= 2 , 0
          429.62 2182.66  614.13         2183.27
Permanent Ineff=
       F       F
Bank Sta=468.1,488.3
XS Rating Curve= 0 ,0
Exp/Cntr(USF)=0,0
Exp/Cntr=0.3,0.1

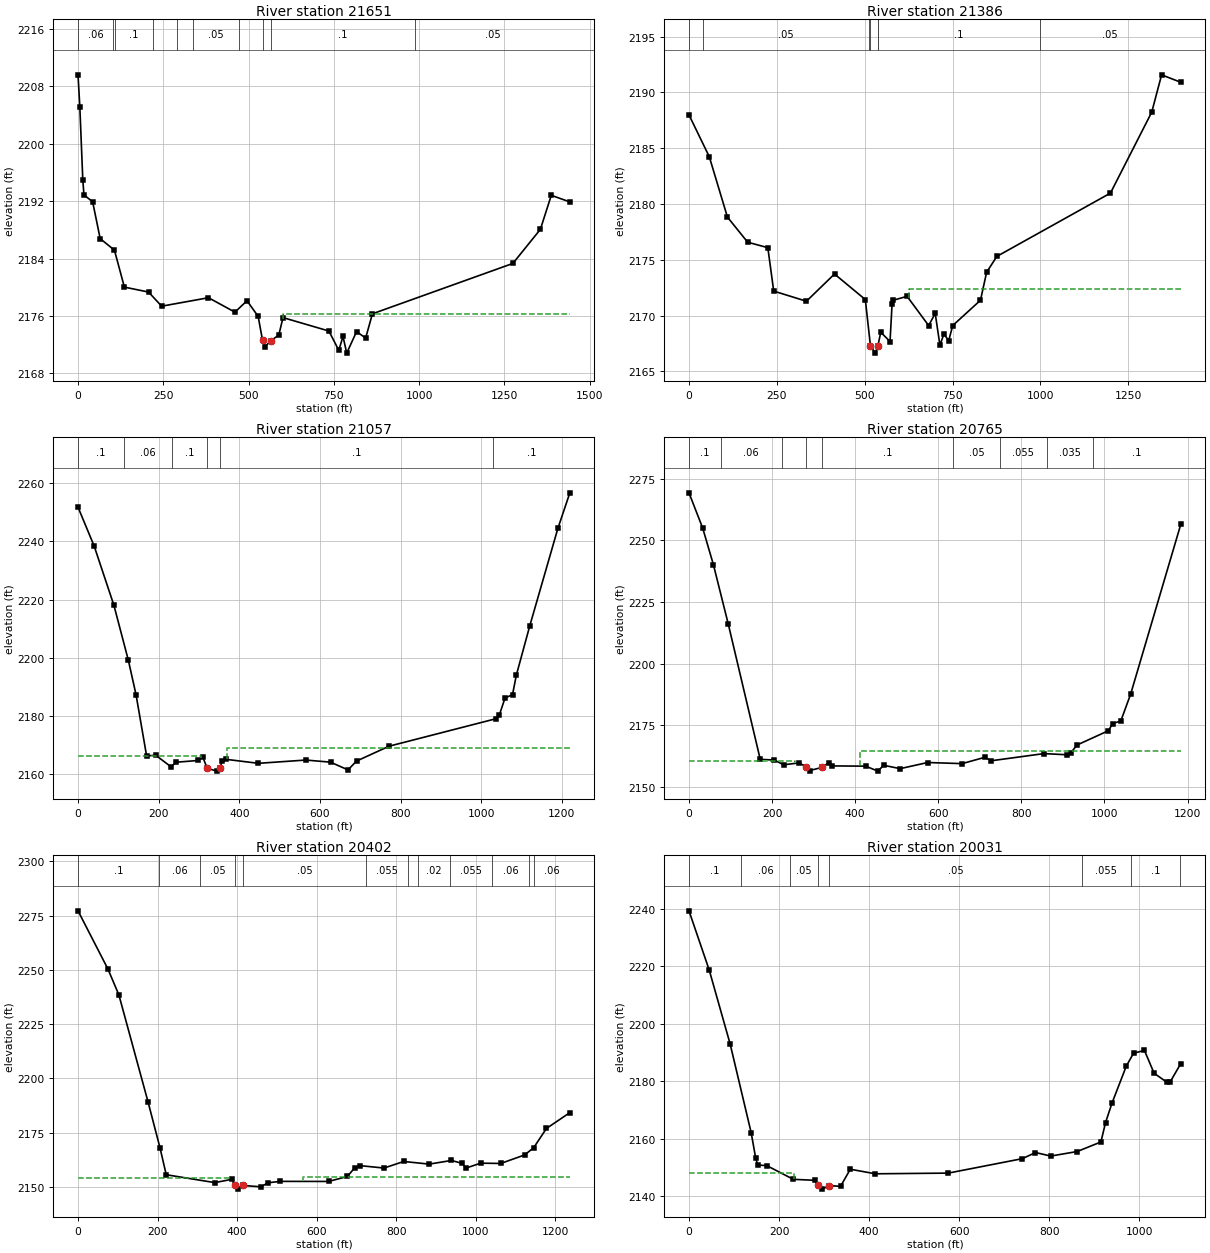
Type RM Length L Ch R = 1 ,21651   ,276.4,265.4,256.5
XS GIS Cut Line= 4
2448118.47202683525470.3919828782448504.47128443525131.510005546
2448615.01567276 525115.200177762449303.65284595524676.647030624
#Sta/Elev= 30
       0 2209.61     5.3 2205.19      14 2195.02    17.4 2192.88    42.9 2191.92
      65 2186.78   106.8 2185.18   135.9 2180.03   206.8 2179.34   245.2 2177.37
   382.5 2178.55     460 2176.54   495.4 2178.13   528.1 2175.95   540.9 2172.63
   548.3 2171.75   564.5 2172.51   588.7 2173.36   600.9 2175.78   735.5 2173.91
   764.5 2171.22   776.8 2173.16   787.7 2170.83   816.6 2173.83   843.2 2172.93
     863 2176.31  1274.8 2183.33  1355.4 2188.08  1387.4 2192.82  1441.8  2191.9
#Mann= 10 ,-1 , 0
       0     .06       0  101.72     .05       0  107.62      .1       0
  218.93     .05       0  289.36      .1       0  336.13     .05       0
  471.11      .1       0   540.9    .045       0   564.5      .1       0
  988.72     .05       0
#XS Ineff= 2 , 0
                          599.66         2176.28
Permanent Ineff=
       F       F
Bank Sta=540.9,564.5
XS Rating Curve= 0 ,0
Exp/Cntr(USF)=0,0
Exp/Cntr=0.3,0.1

Type RM Length L Ch R = 1 ,21386   ,328.9,329.4,330.2
XS GIS Cut Line= 4
2448326.87538187 525700.541774972448611.39126658525405.152671734
2448765.42852901525261.9886278342449321.77487682524716.515498545
#Sta/Elev= 30
       0 2187.98    57.8 2184.23   109.4 2178.82     167 2176.57   224.4 2176.08
   241.1 2172.19   334.2 2171.28   414.1 2173.72   501.8 2171.43   516.32167.311
   530.1 2166.63   537.62167.301   545.8  2168.5   572.1 2167.67     578 2171.07
   581.1 2171.37   620.7 2171.72     682  2169.1   700.7 2170.19   714.1 2167.34
   725.4 2168.34   739.1 2167.75   750.5  2169.1   829.5 2171.37     847 2173.88
   876.2  2175.3  1199.3 2180.97  1316.9 2188.23  1344.9 2191.57  1399.6  2190.9
#Mann= 7 ,-1 , 0
       0     .06       0   40.61     .05       0  513.23      .1       0
   516.3    .045       0   537.6      .1       0  537.64      .1       0
  997.56     .05       0
#XS Ineff= 2 , 0
                          625.21         2172.39
Permanent Ineff=
       F       F
Bank Sta=516.3,537.6
XS Rating Curve= 0 ,0
Exp/Cntr(USF)=0,0
Exp/Cntr=0.3,0.1

Type RM Length L Ch R = 1 ,21057   ,290.8,292,293.6
XS GIS Cut Line= 4
 2448665.7573592525798.4007416862448810.73360619525662.485510135
 2449267.4087842525267.425237096 2449624.4127924525051.773069703
#Sta/Elev= 30
       0 2251.69      40 2238.36    89.1 2217.98   124.9 2199.12   143.9 2187.34
   170.1 2166.35   192.8 2166.56   230.5 2162.62   243.8 2164.18   297.7 2164.77
     309 2166.08   320.4 2162.09   344.8 2161.12     351 2162.03   357.4 2164.45
     368 2165.15   447.3  2163.8   564.9 2164.92   626.1  2164.2   669.5 2161.54
   690.6 2164.57   771.3 2169.67  1035.5 2179.07  1044.8 2180.41  1058.8 2186.18
  1077.5 2187.39  1086.9 2194.04    1120 2210.86  1189.9  2244.4  1219.6 2256.61
#Mann= 6 ,-1 , 0
       0      .1       0  114.59     .06       0   233.4      .1       0
   320.4    .045       0     351      .1       0 1029.72      .1       0
#XS Ineff= 2 , 0
           303.9 2166.28   368.8         2168.92
Permanent Ineff=
       F       F
Bank Sta=320.4,351
XS Rating Curve= 0 ,0
Exp/Cntr(USF)=0,0
Exp/Cntr=0.3,0.1

Type RM Length L Ch R = 1 ,20765   ,361.5,363,362.2
XS GIS Cut Line= 4
2448828.85563706526004.9918936422448982.89289949525881.762083703
2449330.83589226525629.8658545632449773.01344557525290.983877231
#Sta/Elev= 30
       0 2269.24    33.2 2254.85    58.8 2240.11    94.6 2216.03   171.5 2161.23
   204.9 2160.94   227.9 2159.03   265.1 2159.78     281 2158.29   290.8 2156.69
   320.5 2157.98   336.7  2159.9   345.4 2158.56   425.5 2158.47   454.5 2156.45
   468.7 2158.82   508.2 2157.45   574.5 2159.94   657.4 2159.49   712.4 2162.06
   727.5 2160.65   854.3 2163.55   908.9 2163.09     919 2163.87   934.2 2167.04
  1009.7 2172.84  1019.7 2175.75  1039.4 2176.74  1063.3 2187.76  1183.9 2256.53
#Mann= 9 ,-1 , 0
       0      .1       0   76.32     .06       0  223.11      .1       0
     281    .045       0   320.5      .1       0  635.32     .05       0
  748.08    .055       0  860.83    .035       0  973.59      .1       0
#XS Ineff= 2 , 0
          254.38 2160.58  411.76          2164.8
Permanent Ineff=
       F       F
Bank Sta=281,320.5
XS Rating Curve= 0 ,0
Exp/Cntr(USF)=0,0
Exp/Cntr=0.3,0.1

Type RM Length L Ch R = 1 ,20402   ,370.8,370.3,368.9
XS GIS Cut Line= 4
2448944.83663465526253.2637166082449193.10845762 526115.53628197
2449555.54907509525939.7525824982450033.97069014525669.734322485
#Sta/Elev= 30
       0 2277.24    75.4 2250.32   102.8 2238.42     176 2189.12   206.2 2167.86
   221.7 2155.54   343.5 2151.91   387.4 2153.43   394.42150.633   401.3  2148.9
   414.7 2150.59   459.6 2149.97   477.9 2151.83     508 2152.48   629.9 2152.44
   676.9 2154.74     695 2158.65   708.8 2159.73     769 2158.62   818.7 2161.65
   882.7 2160.43   938.4 2162.12   965.2  2160.8   975.2 2158.61  1011.9 2160.87
  1062.4 2160.74  1122.2 2164.64  1145.1 2167.97  1177.3 2176.88  1236.1 2184.18
#Mann= 12 ,-1 , 0
       0      .1       0  202.32     .06       0  307.45     .05       0
   394.4    .045       0   414.7     .05       0  722.88    .055       0
  828.73    .035       0  855.56     .02       0  934.57    .055       0
 1040.42     .06       0 1132.59      .1       0 1146.27     .06       0
#XS Ineff= 2 ,-1
       0  379.88 2154.25  565.861236.095 2154.42
Permanent Ineff=
       F       F
Bank Sta=394.4,414.7
XS Rating Curve= 0 ,0
Exp/Cntr(USF)=0,0
Exp/Cntr=0.3,0.1

Type RM Length L Ch R = 1 ,20031   ,348.2,349.3,349.9
XS GIS Cut Line= 4
2449176.79862983526546.8406167562449332.64809534526450.793853127
2449580.91991831 526313.06641849 2450097.3977982525961.499019546
#Sta/Elev= 30
       0 2239.38      45 2218.71    91.4 2192.97     138 2162.13   147.9  2153.4
   152.6 2150.84   172.9 2150.62   231.6 2145.85   278.7 2145.52   285.92143.815
   296.3 2142.44   311.1 2143.67   336.4  2143.4   358.1 2149.37   413.7 2147.78
   575.6 2148.02   740.2 2153.06   769.2 2155.19   803.1 2153.96   861.8 2155.54
   914.4 2158.87   924.7 2165.62   939.1 2172.44   970.8  2185.3   986.9 2189.81
  1011.1 2190.74  1032.4 2182.83  1060.9 2179.65    1068 2179.75  1091.8 2186.19
#Mann= 8 ,-1 , 0
       0      .1       0   116.5     .06       0  223.23     .05       0
   285.9    .045       0   311.1     .05       0  871.57    .055       0
  981.18      .1       0  1090.8      .1       0
#XS Ineff= 2 , 0
          234.03 2147.91
Permanent Ineff=
       F       F
Bank Sta=285.9,311.1
XS Rating Curve= 0 ,0
Exp/Cntr(USF)=0,0
Exp/Cntr=0.3,0.1

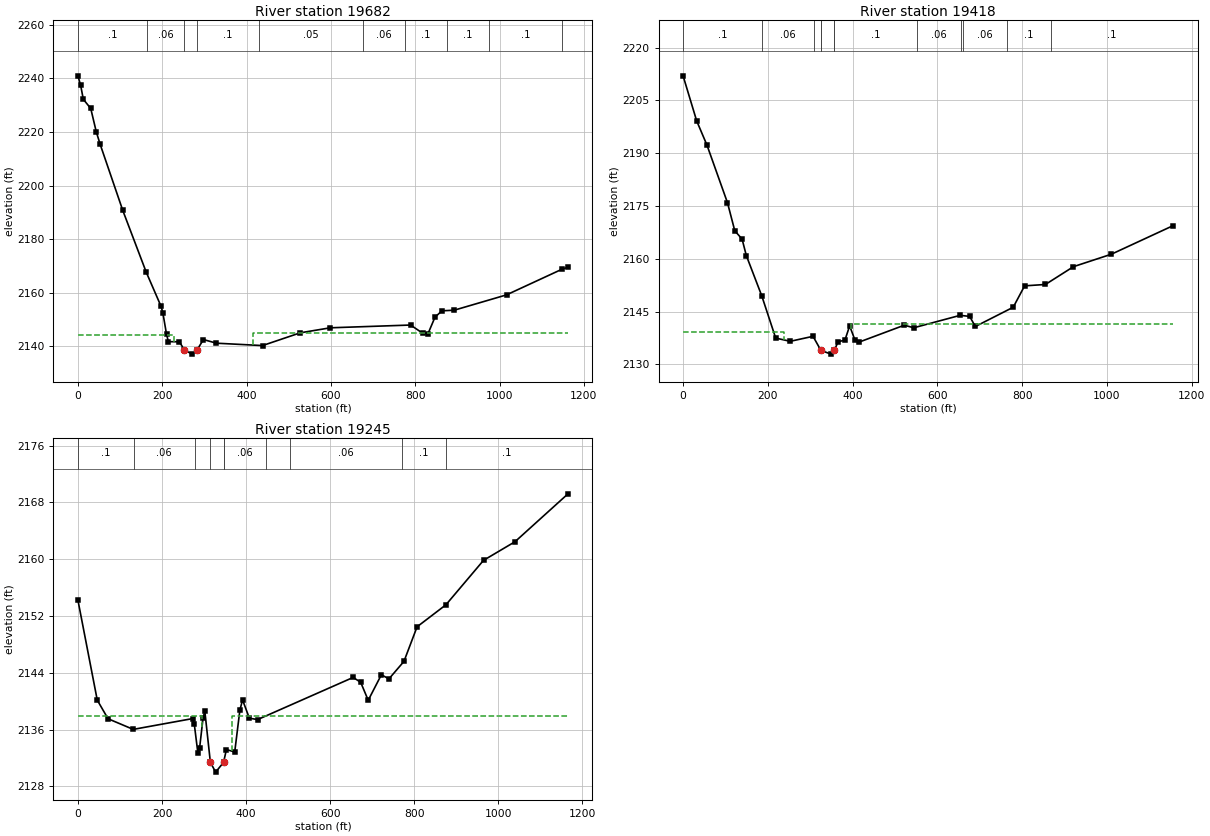
Type RM Length L Ch R = 1 ,19682   ,269.6,264.2,257.7
XS GIS Cut Line= 4
2449271.03319037526827.7320952942449448.62909293526747.995159451
2449798.38428879 526592.145693942450363.79165204526443.545040778
#Sta/Elev= 30
       0 2240.95     6.5 2237.37    12.8  2232.2    30.4 2228.78    43.5 2220.08
    52.3 2215.61   106.3 2190.78   161.9 2167.75     197 2155.03   201.4 2152.57
   210.1  2144.6   214.5  2141.8   240.8 2141.75   252.72138.613   271.4 2137.15
   282.12138.619   297.7 2142.59   328.4 2141.23   437.8 2140.34   527.3  2145.1
   598.6 2146.97   788.9    2148   817.8 2144.93   830.2 2144.76   846.8 2150.93
   863.3 2153.31   892.3 2153.53  1016.4 2159.25  1148.8 2168.88  1162.2 2169.55
#Mann= 10 ,-1 , 0
       0      .1       0  164.53     .06       0   252.7    .045       0
   282.1      .1       0  429.35     .05       0  675.31     .06       0
  775.09      .1       0  874.87      .1       0  974.65      .1       0
  1148.8     .12       0
#XS Ineff= 2 ,-1
       0  227.25  2144.1  415.381162.191  2144.9
Permanent Ineff=
       F       F
Bank Sta=252.7,282.1
XS Rating Curve= 0 ,0
Exp/Cntr(USF)=0,0
Exp/Cntr=0.3,0.1

Type RM Length L Ch R = 1 ,19418   ,181.6,172.5,161.5
XS GIS Cut Line= 4
2449412.38503119527130.3700108792449550.11246582 527034.32324725
2449841.87716288526747.9951594512450360.16724586526488.850117961
#Sta/Elev= 30
       0 2211.96    32.1 2199.15    56.5 2192.23   104.8 2175.89     122 2167.93
   139.2 2165.58   149.2  2160.9   185.6 2149.46   218.5 2137.45   252.8 2136.53
   306.6 2137.95   325.1 2133.96     349 2132.89   356.52133.947     366 2136.42
   381.8 2136.86     393 2140.91   405.6 2136.86   415.4 2136.31   521.9 2141.11
   544.3 2140.38   653.7 2143.91   676.1 2143.61   689.5 2140.74   778.9 2146.21
   805.8 2152.29   854.9 2152.68     921 2157.74  1010.5 2161.28  1156.2  2169.4
#Mann= 12 ,-1 , 0
       0      .1       0  187.32     .06       0  308.94      .1       0
  325.07      .1       0   325.1    .045       0   356.5      .1       0
  356.54      .1       0  552.17     .06       0  656.52     .05       0
  659.77     .06       0  763.83      .1       0  867.88      .1       0
#XS Ineff= 2 ,-1
       0   238.1 2139.22  396.161156.167 2141.36
Permanent Ineff=
       F       F
Bank Sta=325.1,356.5
XS Rating Curve= 0 ,0
Exp/Cntr(USF)=0,0
Exp/Cntr=0.5,0.3

Type RM Length L Ch R = 1 ,19245   ,70.3,72.2,68.1
XS GIS Cut Line= 4
2449615.35177697527311.5903196132449771.20124248527101.374761482
2449872.68461537526766.1171903242450367.41605821526517.845367359
#Sta/Elev= 30
       0 2154.22      46 2140.14    71.6 2137.52   131.6 2136.02   272.6 2137.54
   276.8 2136.74   285.2 2132.73   289.4  2133.4   297.7 2137.69   301.9 2138.54
     3152131.386   327.5    2130   346.42131.377   353.1 2133.18   372.9 2132.84
   385.2 2138.75   391.6 2140.17   407.7  2137.6   427.3  2137.4   654.6 2143.34
   672.5 2142.65   690.4 2140.12   721.7 2143.72   739.6 2143.13   775.4  2145.6
   806.6 2150.47   875.2 2153.57   964.6 2159.83  1039.4 2162.45  1165.5  2169.2
#Mann= 10 ,-1 , 0
       0      .1       0   132.8     .06       0  277.58    .055       0
     315    .045       0   346.4     .06       0  346.43     .06       0
  447.65      .1       0  503.72     .06       0  770.34      .1       0
  874.44      .1       0
#XS Ineff= 2 ,-1
       0     295 2137.88     3661165.499 2137.88
Permanent Ineff=
       F       F
Bank Sta=315,346.4
XS Rating Curve= 0 ,0
Exp/Cntr(USF)=0,0
Exp/Cntr=0.5,0.3