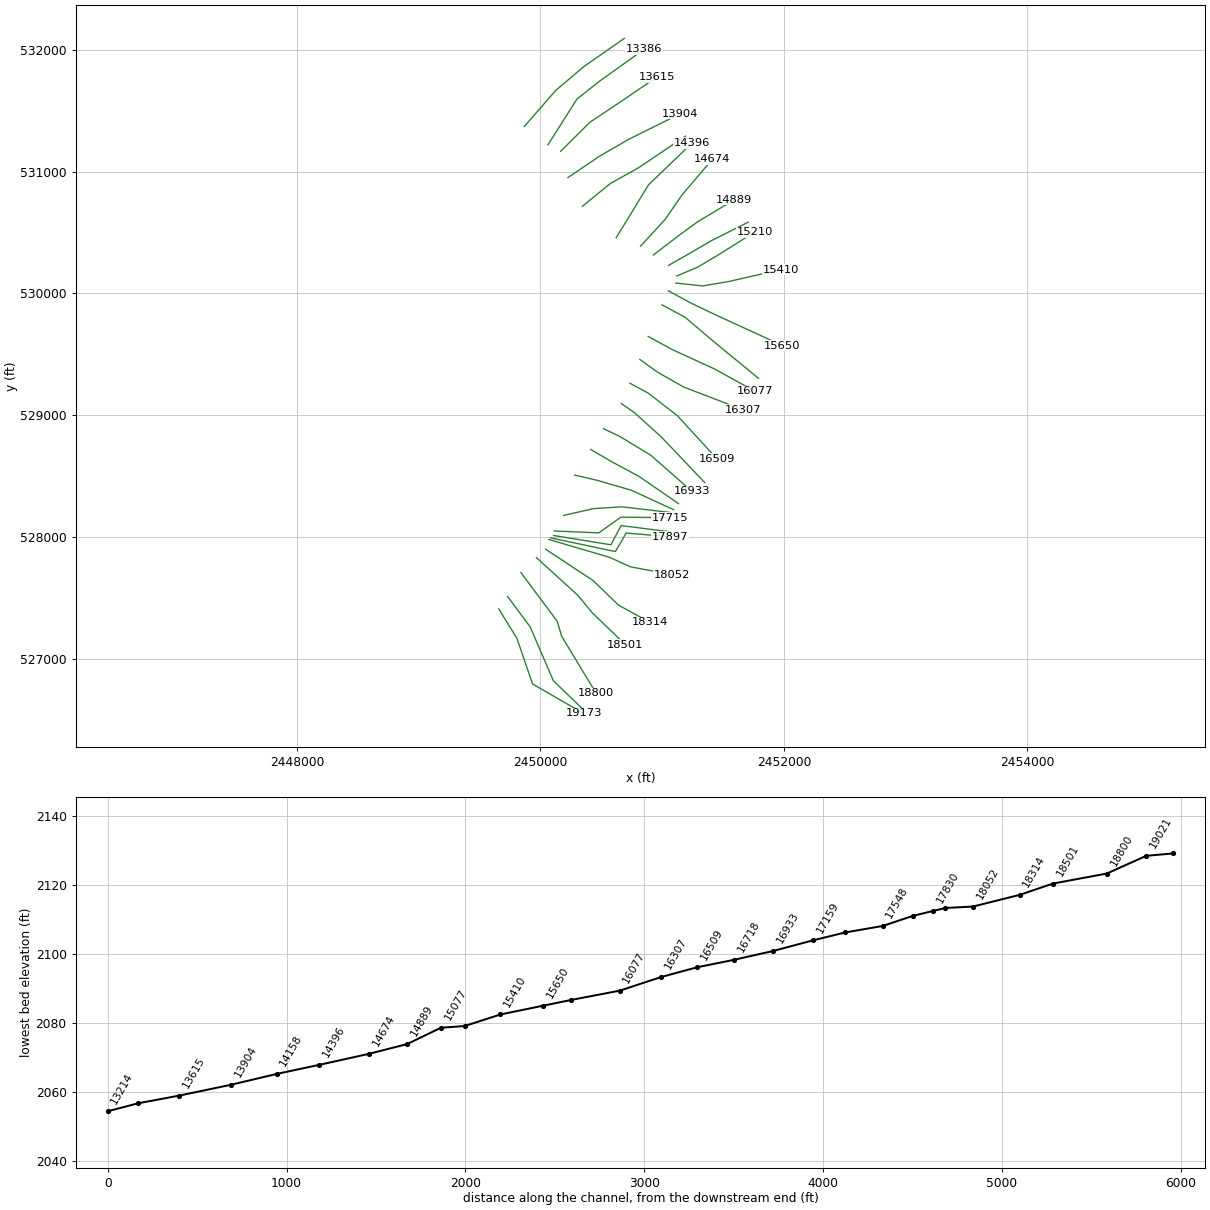
HEC-RAS study BRUSHFK.prj: BRUSHFK

--- BRUSHFK.g01 (geometry) --- (continued)

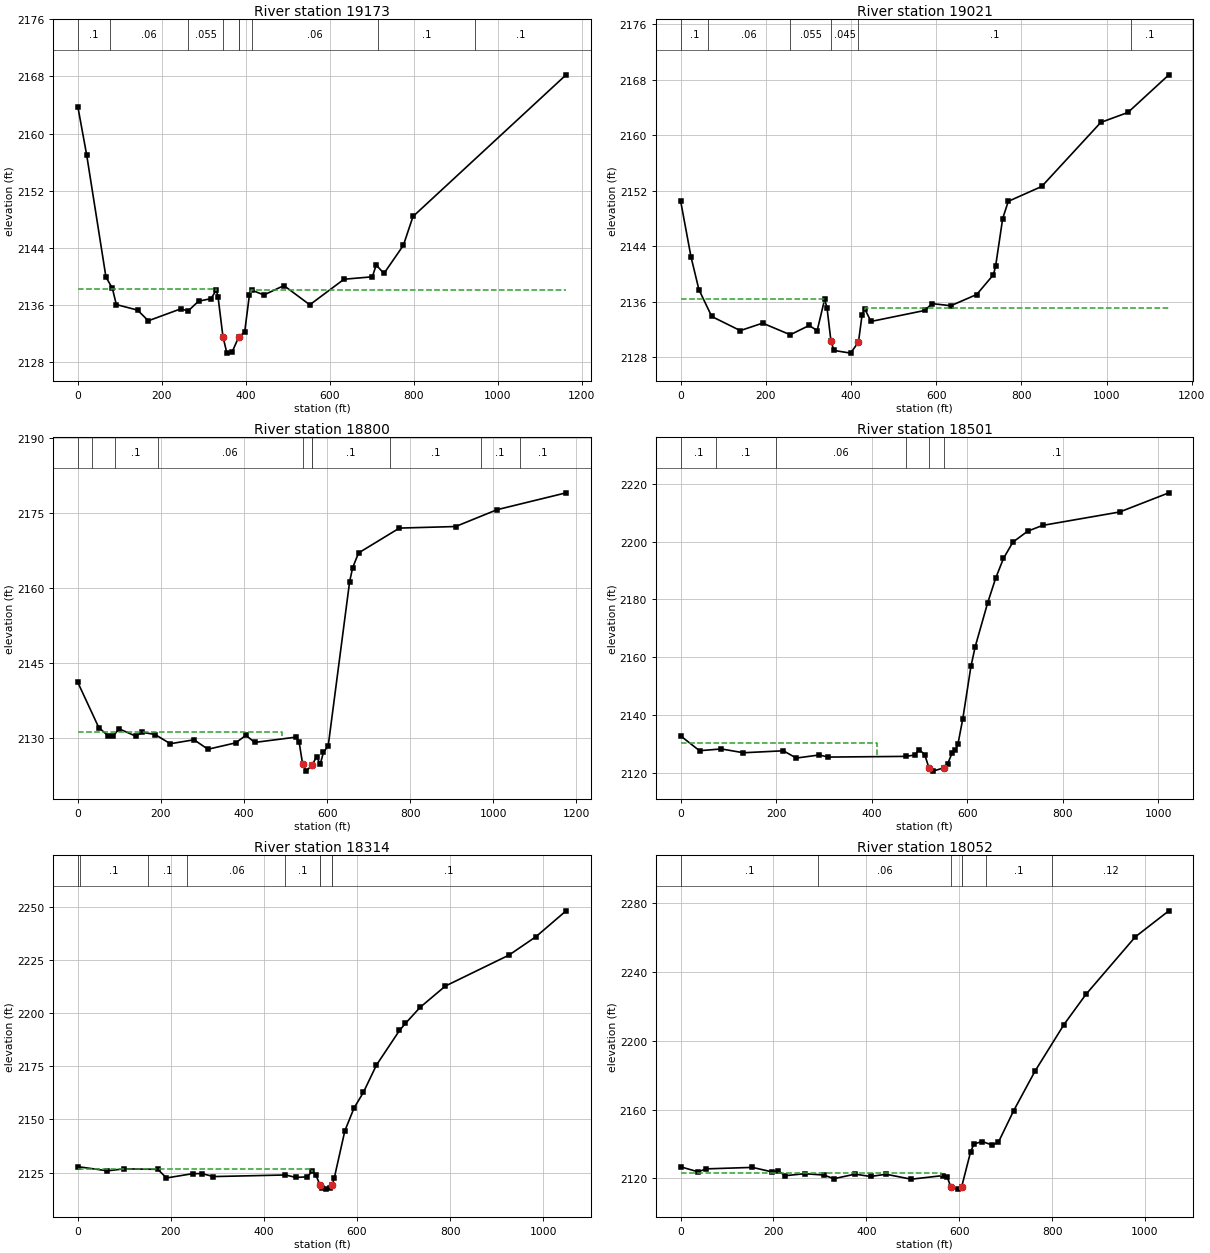
Type RM Length L Ch R = 1 ,19173   ,155.1,151.9,151.1
XS GIS Cut Line= 4
 2449658.5868549527407.9225004272449807.44530422527166.614072626
2449936.11172343526791.488033547 2450354.7306366526550.465022931
#Sta/Elev= 30
       0 2163.78    21.2 2156.96      67  2139.9    82.3 2138.33    91.7 2136.05
   142.2 2135.28   167.9 2133.78   245.6 2135.46   262.5 2135.14   287.5 2136.52
   317.1 2136.88   329.8 2138.06     334 2137.14   345.7 2131.57   355.1 2129.25
   367.7 2129.43   383.5 2131.53   397.4  2132.2   408.7 2137.36   414.3 2138.06
   443.3  2137.4     491 2138.71   552.6 2136.02   634.2  2139.6   701.6 2139.94
   710.8 2141.59   729.3 2140.41   775.5 2144.34   798.5 2148.39  1163.2 2168.23
#Mann= 9 ,-1 , 0
       0      .1       0  76.283     .06       0 262.472    .055       0
   345.7    .045       0   383.5    .055       0  383.52    .055       0
 415.007     .06       0 715.455      .1       0 946.236      .1       0
#XS Ineff= 2 ,-1
       0  330.11  2138.2  411.551163.154 2138.12
Permanent Ineff=
       F       F
Bank Sta=345.7,383.5
XS Rating Curve= 0 ,0
Exp/Cntr(USF)=0,0
Exp/Cntr=0.5,0.3

Type RM Length L Ch R = 1 ,19021   ,223.6,220.6,222.9
XS GIS Cut Line= 4
2449731.05656438527509.3874593062449916.17748947527260.848633167
2450106.45881364526818.6710798572450361.97944895526572.211459979
#Sta/Elev= 30
       0 2150.54    24.4 2142.46      43 2137.72    73.1 2133.84   140.1  2131.8
   192.6 2132.88   257.5  2131.2   301.7 2132.54   320.7 2131.81   338.2 2136.32
   343.8 2135.08   352.9 2130.34   359.9 2128.94   399.1 2128.55   417.6 2130.15
     426 2134.02   432.1 2134.96     447 2133.12   573.3 2134.71   590.4  2135.7
   634.3 2135.39   695.2 2137.01   734.4 2139.86   739.6 2141.11   756.2 2147.98
   769.3 2150.46   847.9 2152.61   986.5 2161.85  1050.3 2163.29  1146.3 2168.72
#Mann= 6 ,-1 , 0
       0      .1       0  64.449     .06       0 257.483    .055       0
   352.9    .045       0   417.6      .1       01057.249      .1       0
#XS Ineff= 2 ,-1
       0  336.17 2136.35  434.081146.298 2135.09
Permanent Ineff=
       F       F
Bank Sta=352.9,417.6
XS Rating Curve= 0 ,0
Exp/Cntr(USF)=0,0
Exp/Cntr=0.3,0.1

Type RM Length L Ch R = 1 ,18800   ,293.6,299.9,303.8
XS GIS Cut Line= 4
2449839.58619549527707.2950830722450137.26626612527307.965913438
2450175.32253095527182.9239004122450458.02621258526715.375503879
#Sta/Elev= 30
       0 2141.11    50.4  2132.1    72.2  2130.5    85.6 2130.41      99 2131.86
   139.1 2130.39   155.2 2131.15     186 2130.71   222.6 2128.87   279.7 2129.66
   313.2 2127.77   379.8 2129.04   404.6 2130.55   425.6 2129.13   524.3 2130.18
   532.6 2129.23     541 2124.82   549.4  2123.4   564.2 2124.63   574.5 2126.26
   583.5 2124.81   591.2 2127.14   602.7 2128.48   654.2 2161.25   661.5 2164.02
   675.6 2166.96     774 2171.93   909.3 2172.24  1008.9  2175.6  1175.2 2178.97
#Mann= 10 ,-1 , 0
       0      .1       0  33.988      .1       0  88.297      .1       0
 192.682     .06       0     541    .045       0   564.2    .045       0
 564.231      .1       0 751.353      .1       0 969.204      .1       0
1063.533      .1       0
#XS Ineff= 2 , 0
          492.18 2131.18
Permanent Ineff=
       F       F
Bank Sta=541,564.2
XS Rating Curve= 0 ,0
Exp/Cntr(USF)=0,0
Exp/Cntr=0.3,0.1

Type RM Length L Ch R = 1 ,18501   ,184.4,187,188.1
XS GIS Cut Line= 4
 2449967.6487506527829.5687526672450307.61335633527519.993674657
2450425.40655701527376.8296307572450697.23702011 527115.87238618
#Sta/Elev= 30
       0 2132.73    39.6 2127.58    85.3 2128.19   131.5 2126.87   215.2 2127.55
   242.2 2125.03   290.1  2126.1   308.9 2125.37     471 2125.61   489.9 2126.07
   499.7 2127.97   511.1 2126.17   519.6 2121.75   528.2  2120.5   550.9 2121.63
   559.2 2123.09   567.9 2126.64   575.2 2127.72   580.4 2129.74   590.7 2138.65
   607.7 2156.78   616.6  2163.6   642.5  2178.7   659.5 2187.39   675.8 2194.22
   695.6  2199.9   726.7  2203.7   757.8 2205.69   919.1 2210.34    1022 2216.98
#Mann= 6 ,-1 , 0
       0      .1       0  74.875      .1       0 198.945     .06       0
 471.021      .1       0   519.6    .045       0   550.9      .1       0
#XS Ineff= 2 , 0
          411.55 2130.35
Permanent Ineff=
       F       F
Bank Sta=519.6,550.9
XS Rating Curve= 0 ,0
Exp/Cntr(USF)=0,0
Exp/Cntr=0.3,0.1

Type RM Length L Ch R = 1 ,18314   ,254.3,261.4,265.7
XS GIS Cut Line= 4
2450043.76128027527897.9208758722450432.65536936527641.411281508
2450642.87092749527438.444535726 2450898.3915628527298.904898001
#Sta/Elev= 30
       0 2127.78    63.6 2125.84    99.4 2126.75   171.8 2126.53   190.5 2122.47
   246.9 2124.49     267 2124.53   291.1 2123.12   446.1 2123.87   468.8 2122.72
   491.8 2122.98   504.1 2125.51   511.6  2123.8   520.12119.328   524.4 2117.93
   534.2 2117.21   541.1 2117.59   546.6 2119.21   551.2 2122.58   573.8 2144.67
   593.6 2155.42   613.5 2162.71   641.7 2175.62   691.2 2191.91   703.9 2195.22
   735.7 2202.83   789.8 2212.82   926.6 2227.41   984.6 2236.09  1049.2 2248.24
#Mann= 9 ,-1 , 0
       0      .1       0   4.341      .1       0 151.594      .1       0
 235.326     .06       0   446.1      .1       0 520.051      .1       0
   520.1    .045       0   546.6      .1       0 546.618      .1       0
#XS Ineff= 2 , 0
          503.39 2126.51
Permanent Ineff=
       F       F
Bank Sta=520.1,546.6
XS Rating Curve= 0 ,0
Exp/Cntr(USF)=0,0
Exp/Cntr=0.3,0.1

Type RM Length L Ch R = 1 ,18052   ,128.9,154.7,182.2
XS GIS Cut Line= 4
2450070.38589779527978.6215597752450568.57060091527831.692605679
 2450740.7298942527753.7678729232451077.79966845527690.340764866
#Sta/Elev= 30
       0 2126.79    37.9 2123.84    54.6 2125.58   154.7 2126.44   196.1 2123.88
   209.4 2124.47   225.5 2121.63   267.4 2122.78     309 2121.98   329.8 2119.85
   375.7 2122.52     409 2121.16   442.4 2122.46   496.6 2119.58   565.7 2121.71
   574.5 2120.62   582.1 2114.92   596.4 2113.81   605.2 2115.12   624.4 2135.38
   631.6 2139.98   649.1 2141.49   671.1 2139.45   684.2    2141   717.3 2159.42
   763.3 2182.44   825.6 2209.49   872.7 2226.96   979.1 2260.42  1051.4 2275.57
#Mann= 7 ,-1 , 0
       0      .1       0  296.36     .06       0   582.1    .045       0
   605.2     .06       0 605.209     .06       0 657.664      .1       0
 799.969     .12       0
#XS Ineff= 2 , 0
          560.58 2123.17
Permanent Ineff=
       F       F
Bank Sta=582.1,605.2
XS Rating Curve= 0 ,0
Exp/Cntr(USF)=0,0
Exp/Cntr=0.5,0.3

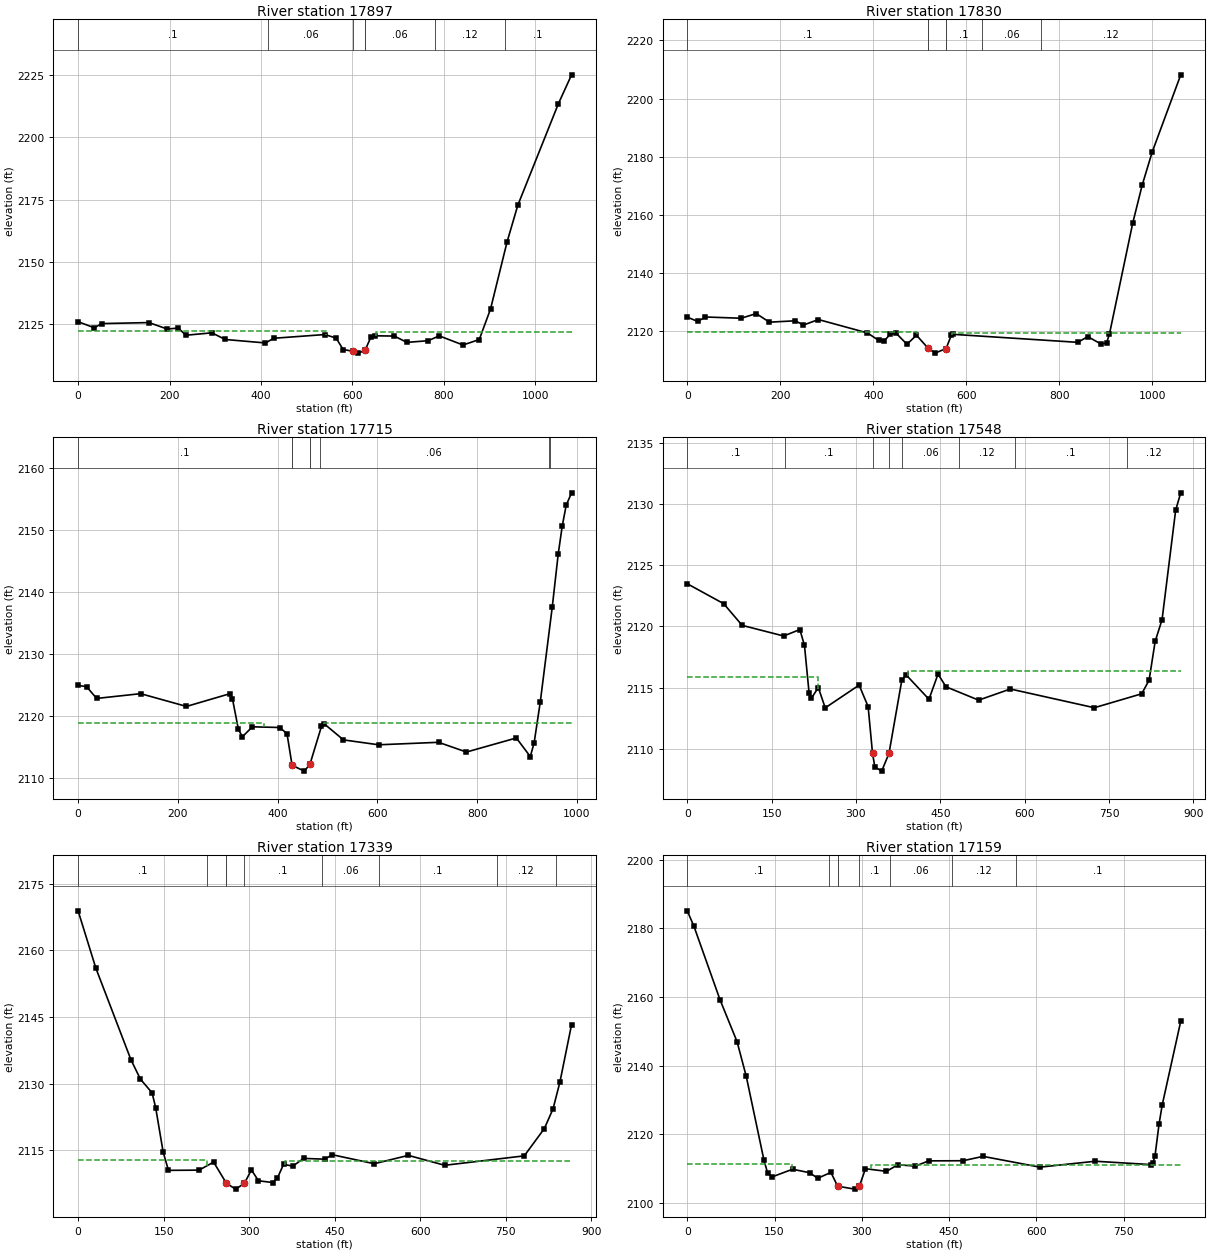
Type RM Length L Ch R = 1 ,17897   ,63.8,67.4,69.2
XS GIS Cut Line= 5
2450084.08190214 527991.980703212450615.20891845527879.227019585
2450630.18550588527902.3685260852450704.48583246528031.034945286
2451063.30204375528002.039695888
#Sta/Elev= 30
       0    2126    35.4 2123.55    51.8 2125.24     155 2125.64   194.9 2123.05
     219 2123.44   235.8 2120.57   292.7 2121.53   321.7 2118.86   409.7 2117.47
     428 2119.35   539.5 2120.84   564.2 2119.44   579.6 2114.83   600.6 2114.17
   612.7 2113.39   627.6 2114.51   640.4 2119.89   649.7 2120.34   691.6 2120.23
   718.9 2117.71   765.5 2118.36   789.6 2120.32   841.8 2116.65   877.3 2118.84
     902 2131.14   938.1 2158.01   961.5 2172.67  1050.4 2213.46  1079.1    2225
#Mann= 7 ,-1 , 0
       0      .1       0 415.726     .06       0   600.6    .045       0
   627.6     .06       0 627.639     .06       0 780.746     .12       0
 932.979      .1       0
#XS Ineff= 2 ,-1
       0  541.52 2122.37  651.551079.093 2121.75
Permanent Ineff=
       F       F
Bank Sta=600.6,627.6
XS Rating Curve= 0 ,0
Exp/Cntr(USF)=0,0
Exp/Cntr=0.5,0.3

Type RM Length L Ch R = 1 ,17830   ,124.3,114.7,102.1
XS GIS Cut Line= 4
2450108.39532796528011.2412153472450579.44381943527934.988181657
2450662.80516145528092.6498502552451065.11424684 528041.90816381
#Sta/Elev= 30
       0 2124.92    22.6 2123.43    38.8 2124.97   115.8 2124.54   148.3 2126.14
   176.6 2123.19   232.5 2123.66   249.6 2122.19     282 2124.09   387.3 2119.49
   411.6 2116.93   423.8 2116.81     436 2118.98   448.8 2119.42   472.4  2115.6
   492.8 2118.71   517.8 2114.23   532.8 2112.55   556.5 2114.13   567.6 2118.64
   571.3 2119.01   839.6 2116.26   861.1 2118.22   889.3 2115.71   901.4 2116.03
   907.7 2119.09   957.8 2157.26     978 2170.23   999.4 2181.56    1061 2208.19
#Mann= 7 ,-1 , 0
       0      .1       0 517.793      .1       0   517.8    .045       0
   556.5      .1       0 556.505      .1       0 633.459     .06       0
 760.868     .12       0
#XS Ineff= 2 , 0
             493 2119.88  570.11         2119.53
Permanent Ineff=
       F       F
Bank Sta=517.8,556.5
XS Rating Curve= 0 ,0
Exp/Cntr(USF)=0,0
Exp/Cntr=0.5,0.3

Type RM Length L Ch R = 1 ,17715   ,181.4,167.8,156.6
XS GIS Cut Line= 4
2450113.62499716528048.1889201652450479.77264963528032.847148373
2450660.99295836528161.5135675742451061.48984066528157.889161399
#Sta/Elev= 30
       0 2124.93    17.1 2124.71    37.2 2122.82   125.3 2123.59   217.3 2121.53
   304.9  2123.6   309.4 2122.78   321.4 2117.82   329.4 2116.64   349.4 2118.24
   404.5 2118.13   418.8 2117.12     429 2112.03   453.5 2111.09   464.72112.179
   487.9 2118.32   492.8 2118.76     532 2116.13   602.5 2115.34   722.5 2115.74
   778.5 2114.17   878.5 2116.44   906.5 2113.44   914.2 2115.67   926.5 2122.26
   950.5 2137.57   962.5 2146.15   970.5 2150.64   978.5 2154.01   989.2    2156
#Mann= 8 ,-1 , 0
       0      .1       0 428.982      .1       0     429    .045       0
   464.7      .1       0 464.737      .1       0 484.819     .06       0
 943.071     .12       0 946.487      .1       0
#XS Ineff= 2 , 0
          372.56 2118.88  492.42          2118.8
Permanent Ineff=
       F       F
Bank Sta=429,464.7
XS Rating Curve= 0 ,0
Exp/Cntr(USF)=0,0
Exp/Cntr=0.3,0.1

Type RM Length L Ch R = 1 ,17548   ,215.1,208.8,200.9
XS GIS Cut Line= 4
2450191.63235874528176.0111922732450436.27977553 528232.18948798
 2450670.0539738528246.6871126792451059.67763757528201.382035496
#Sta/Elev= 30
       0 2123.48    64.8 2121.85    97.6 2120.08   171.5 2119.21   200.2 2119.74
   208.4 2118.44   216.6 2114.56   220.7 2114.12     233    2115   245.3 2113.34
   305.6  2115.2   321.6 2113.44   329.42109.626   333.6 2108.51   345.7 2108.17
   358.7 2109.62   381.7 2115.65   389.7 2116.01   429.8 2114.04   445.9  2116.1
   460.1 2115.06   518.1 2113.97   574.5 2114.88   723.8 2113.35   808.1 2114.49
   821.2  2115.6     832 2118.77   844.3 2120.55   868.5  2129.5   877.5 2130.91
#Mann= 8 ,-1 , 0
       0      .1       0  174.09      .1       0   329.4    .045       0
   358.7      .1       0  381.63     .06       0  483.46     .12       0
  582.92      .1       0  781.76     .12       0
#XS Ineff= 2 ,-1
       0  231.77 2115.85  391.75877.4868 2116.38
Permanent Ineff=
       F       F
Bank Sta=329.4,358.7
XS Rating Curve= 0 ,0
Exp/Cntr(USF)=0,0
Exp/Cntr=0.3,0.1

Type RM Length L Ch R = 1 ,17339   ,182.2,180.3,175.2
XS GIS Cut Line= 4
2450280.43031002528507.6443572562450467.08722802528464.151483159
2450747.97870655528382.6023442292451094.10949623528223.128472544
#Sta/Elev= 30
       0 2168.86    31.1 2155.99    92.7 2135.37   109.2 2131.03   129.7 2127.95
     136 2124.63   149.1 2114.65   158.4 2110.51   212.1 2110.56   237.6 2112.37
   260.22107.573   276.3 2106.29   291.72107.593   303.8 2110.62   316.3 2108.17
   341.2 2107.77   349.6 2108.82   360.3 2111.88   376.4 2111.45   395.4  2113.2
   432.9 2113.02   445.4 2114.03   519.2    2112     579 2113.88   642.8 2111.65
   782.3 2113.77   817.5 2119.91   832.7 2124.33   844.8 2130.36   865.2 2143.28
#Mann= 9 ,-1 , 0
       0      .1       0  226.71      .1       0  260.15      .1       0
   260.2    .045       0   291.7      .1       0  426.82     .06       0
  528.17      .1       0  734.33     .12       0  837.41      .1       0
#XS Ineff= 2 , 0
          225.55 2112.93  362.35         2112.66
Permanent Ineff=
       F       F
Bank Sta=260.2,291.7
XS Rating Curve= 0 ,0
Exp/Cntr(USF)=0,0
Exp/Cntr=0.3,0.1

Type RM Length L Ch R = 1 ,17159   ,222.1,225.1,220.6
XS GIS Cut Line= 4
 2450412.7211354528717.8599153872450590.31703795528614.564339408
2450809.59361152528496.7711387322451133.97796416528273.870158989
#Sta/Elev= 30
       0 2185.15    11.6 2180.58    56.3  2159.2    85.6 2146.98   101.4 2136.85
   131.9 2112.35   138.2 2108.63   145.8 2107.57   180.9  2109.8   210.5 2108.78
   224.1 2107.16   246.8 2108.88   258.42104.857   287.7    2104   295.82104.869
   306.2 2109.95   342.2 2109.19   362.1  2111.1   392.1 2110.72   414.8 2112.24
   473.8 2112.28   508.3 2113.55     606 2110.41   701.1 2112.13   796.7 2111.16
   800.3  2111.7   803.8 2113.75   810.8 2123.07   816.1  2128.5     848 2152.96
#Mann= 8 ,-1 , 0
       0      .1       0  244.11      .1       0  258.38      .1       0
   258.4    .045       0   295.8      .1       0  349.17     .06       0
  454.23     .12       0  564.07      .1       0
#XS Ineff= 2 ,-1
       0  179.76 2111.43     316847.9501 2110.93
Permanent Ineff=
       F       F
Bank Sta=258.4,295.8
XS Rating Curve= 0 ,0
Exp/Cntr(USF)=0,0
Exp/Cntr=0.3,0.1

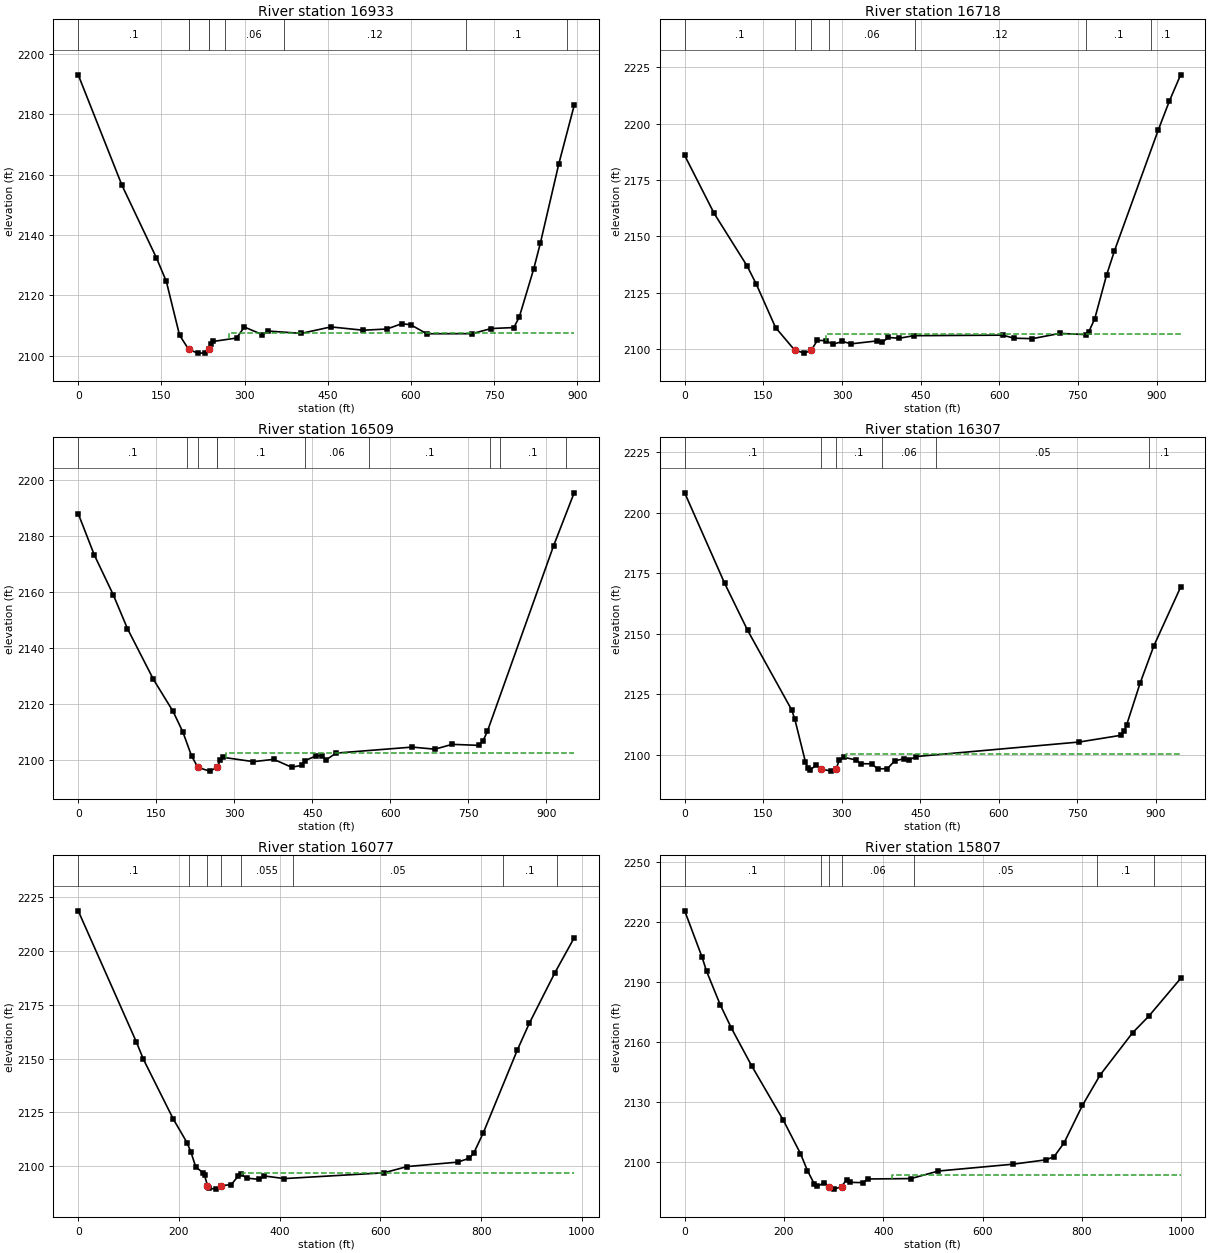
Type RM Length L Ch R = 1 ,16933   ,219.3,215.8,210.9
XS GIS Cut Line= 4
2450519.64111755528888.2070055962450651.93194292 528824.77989754
2450903.82817206528672.5548382032451244.52235248528373.541328793
#Sta/Elev= 30
       0 2193.02    78.9 2156.44     141 2132.43   158.9 2124.63   182.7 2106.84
   199.22102.111   215.4 2100.88   229.4 2100.92   235.12102.095   238.8 2103.99
   243.9 2104.76   285.5 2105.88   299.6 2109.52   332.3 2106.98   342.4 2108.19
   402.4 2107.42   455.6 2109.56   514.1 2108.46   556.7 2108.87   583.2  2110.6
   599.3  2110.3   628.5 2107.29   710.4 2107.32   744.7 2109.02   785.5 2109.35
   795.3 2112.79   821.3 2128.71   833.4 2137.32   866.6 2163.52   894.3 2182.87
#Mann= 9 ,-1 , 0
       0      .1       0  199.18      .1       0   199.2    .045       0
   235.1      .1       0  235.14      .1       0  263.88     .06       0
  370.95     .12       0   699.3      .1       0  881.09      .1       0
#XS Ineff= 2 , 0
                          271.91         2107.54
Permanent Ineff=
       F       F
Bank Sta=199.2,235.1
XS Rating Curve= 0 ,0
Exp/Cntr(USF)=0,0
Exp/Cntr=0.3,0.1

Type RM Length L Ch R = 1 ,16718   ,206.6,208.8,209.9
XS GIS Cut Line= 4
2450664.61736454529094.798157553 2450769.7251436 529022.31003406
2450994.43832643528819.3432882782451349.63013155528446.029452286
#Sta/Elev= 30
       0 2185.88      56 2160.29   119.2 2136.88   136.5 2128.93   173.3 2109.69
   209.62099.717   228.3 2098.35   241.72099.712     253    2104     270 2103.87
     282 2102.22   300.7 2103.52   317.7 2102.47   365.9 2103.73   377.2 2103.25
   388.5 2105.28   409.3 2104.94   436.7 2106.07   606.4 2106.31   628.2 2104.96
     663 2104.75   715.3 2107.08   764.9 2106.57   770.5 2107.72   781.9 2113.46
   804.5 2132.86   819.7  2143.7   903.5 2197.34   924.2 2209.87   945.8 2221.57
#Mann= 7 ,-1 , 0
       0      .1       0   209.6    .045       0   241.7      .1       0
  274.56     .06       0  438.57     .12       0   764.9      .1       0
  889.61      .1       0
#XS Ineff= 1 ,-1
  270.23945.7767 2106.86
Permanent Ineff=
       F
Bank Sta=209.6,241.7
XS Rating Curve= 0 ,0
Exp/Cntr(USF)=0,0
Exp/Cntr=0.3,0.1

Type RM Length L Ch R = 1 ,16509   ,195.7,201.5,203.3
XS GIS Cut Line= 4
2450735.29328494529261.520841588 2450883.8939381529181.783905745
2451124.91694872528995.1269877492451449.30130135528641.747385719
#Sta/Elev= 30
       0 2188.07    30.9 2173.32    67.5 2159.04    94.7 2146.99   144.6 2128.89
   182.4 2117.44   201.2 2110.09   217.8 2101.59     2302097.478   252.6 2096.15
   267.2 2097.46   273.4 2100.18   278.5 2101.08   336.7 2099.53   375.9 2100.36
     410 2097.55   430.3 2098.23   435.3 2099.87   457.9 2101.63   469.3 2101.59
   476.2 2100.13   495.5 2102.58   641.8 2104.73   685.6 2103.98   718.7 2105.71
   769.4 2105.35   777.9 2106.87   786.4 2110.35   913.6 2176.55   953.2 2195.49
#Mann= 10 ,-1 , 0
       0      .1       0  209.83      .1       0     230    .045       0
   267.2      .1       0  267.23      .1       0  435.95     .06       0
  557.95      .1       0  791.77     .12       0  810.85      .1       0
   937.3      .1       0
#XS Ineff= 1 ,-1
  283.21953.1808 2102.46
Permanent Ineff=
       F
Bank Sta=230,267.2
XS Rating Curve= 0 ,0
Exp/Cntr(USF)=0,0
Exp/Cntr=0.3,0.1

Type RM Length L Ch R = 1 ,16307   ,227.3,230.8,231.3
XS GIS Cut Line= 4
2450816.84242387529457.2387750212450960.00646777529353.943199042
2451175.65863516529230.7133891032451663.14126566529044.056471108
#Sta/Elev= 30
       0 2208.21    76.3 2170.86   120.2 2151.42   204.2 2118.63   210.1 2114.89
   230.6 2097.09     235 2094.62   239.6 2093.81   251.1 2095.75   259.9 2094.25
   279.4 2093.31   289.3 2094.35   294.9  2097.7   304.1 2099.03   327.1  2097.9
   336.3 2096.38   356.7 2096.33   368.6 2094.25     387 2094.32   400.8 2097.54
   418.3 2098.39   428.2 2097.87   441.1 2099.31   753.7 2105.34   832.9  2108.1
   839.1 2109.75   843.7  2112.3   869.4 2129.54   895.6 2144.94   946.9 2169.27
#Mann= 6 ,-1 , 0
       0      .1       0   259.9    .045       0   289.3      .1       0
  376.48     .06       0  480.03     .05       0   885.8      .1       0
#XS Ineff= 2 , 0
                          307.52         2100.58
Permanent Ineff=
       F       F
Bank Sta=259.9,289.3
XS Rating Curve= 0 ,0
Exp/Cntr(USF)=0,0
Exp/Cntr=0.3,0.1

Type RM Length L Ch R = 1 ,16077   ,273.7,269.2,264.5
XS GIS Cut Line= 4
2450885.70614119529645.707896104 2451085.0484808529536.975710863
2451429.36706739529379.3140422652451761.00023237529196.281530444
#Sta/Elev= 30
       0  2218.7   115.1 2157.95   129.6 2149.62   188.6 2121.99   216.1 2110.92
     224 2106.43   233.3 2099.66     248 2096.95   250.9 2095.73   256.62091.026
   259.7 2089.76   272.9 2089.36   284.2 2091.02   303.7  2091.4   316.9 2095.23
   323.5 2096.18   334.5 2094.48   359.7 2093.89   369.7 2095.47   409.3 2094.26
   607.1 2096.95     653 2099.85   753.5 2101.91   776.4 2103.72   785.5 2106.21
   804.3 2115.57     872 2154.13   895.6 2166.45     946 2189.77   984.6 2206.14
#Mann= 8 ,-1 , 0
       0      .1       0  220.48      .1       0   256.6    .045       0
   284.2      .1       0  323.64    .055       0  426.65     .05       0
  844.29      .1       0  949.77     .12       0
#XS Ineff= 1 ,-1
  325.04984.5563 2097.06
Permanent Ineff=
       F
Bank Sta=256.6,284.2
XS Rating Curve= 0 ,0
Exp/Cntr(USF)=0,0
Exp/Cntr=0.3,0.1

Type RM Length L Ch R = 1 ,15807   ,152.1,156.9,161.3
XS GIS Cut Line= 4
2450999.87493569529904.8529375932451188.34405678529803.369564702
2451416.68164578529609.4638343572451791.80768486 529301.38930951
#Sta/Elev= 30
       0  2225.5    35.1 2202.34    44.1 2195.36    71.5  2178.7    94.1    2167
     135 2148.16   198.5 2121.15   233.3 2104.39   247.3 2095.92   261.5 2089.09
   267.2 2088.07   281.4 2089.91     2912087.959   301.2 2086.69   316.22087.957
     326 2091.42   332.4 2090.09   358.9 2089.92   369.3 2091.75   455.8 2091.95
   511.1 2095.72   661.2 2099.12   728.5 2101.33   744.3 2102.94   764.2 2109.75
   801.1 2128.41   837.2 2143.73   902.1 2164.63   934.7  2172.9     999 2191.77
#Mann= 7 ,-1 , 0
       0      .1       0  274.92     .06       0     291    .045       0
   316.2     .06       0  461.52     .05       0  830.53      .1       0
  945.43     .12       0
#XS Ineff= 2 , 0
                          418.32         2093.87
Permanent Ineff=
       F       F
Bank Sta=291,316.2
XS Rating Curve= 0 ,0
Exp/Cntr(USF)=0,0
Exp/Cntr=0.3,0.1

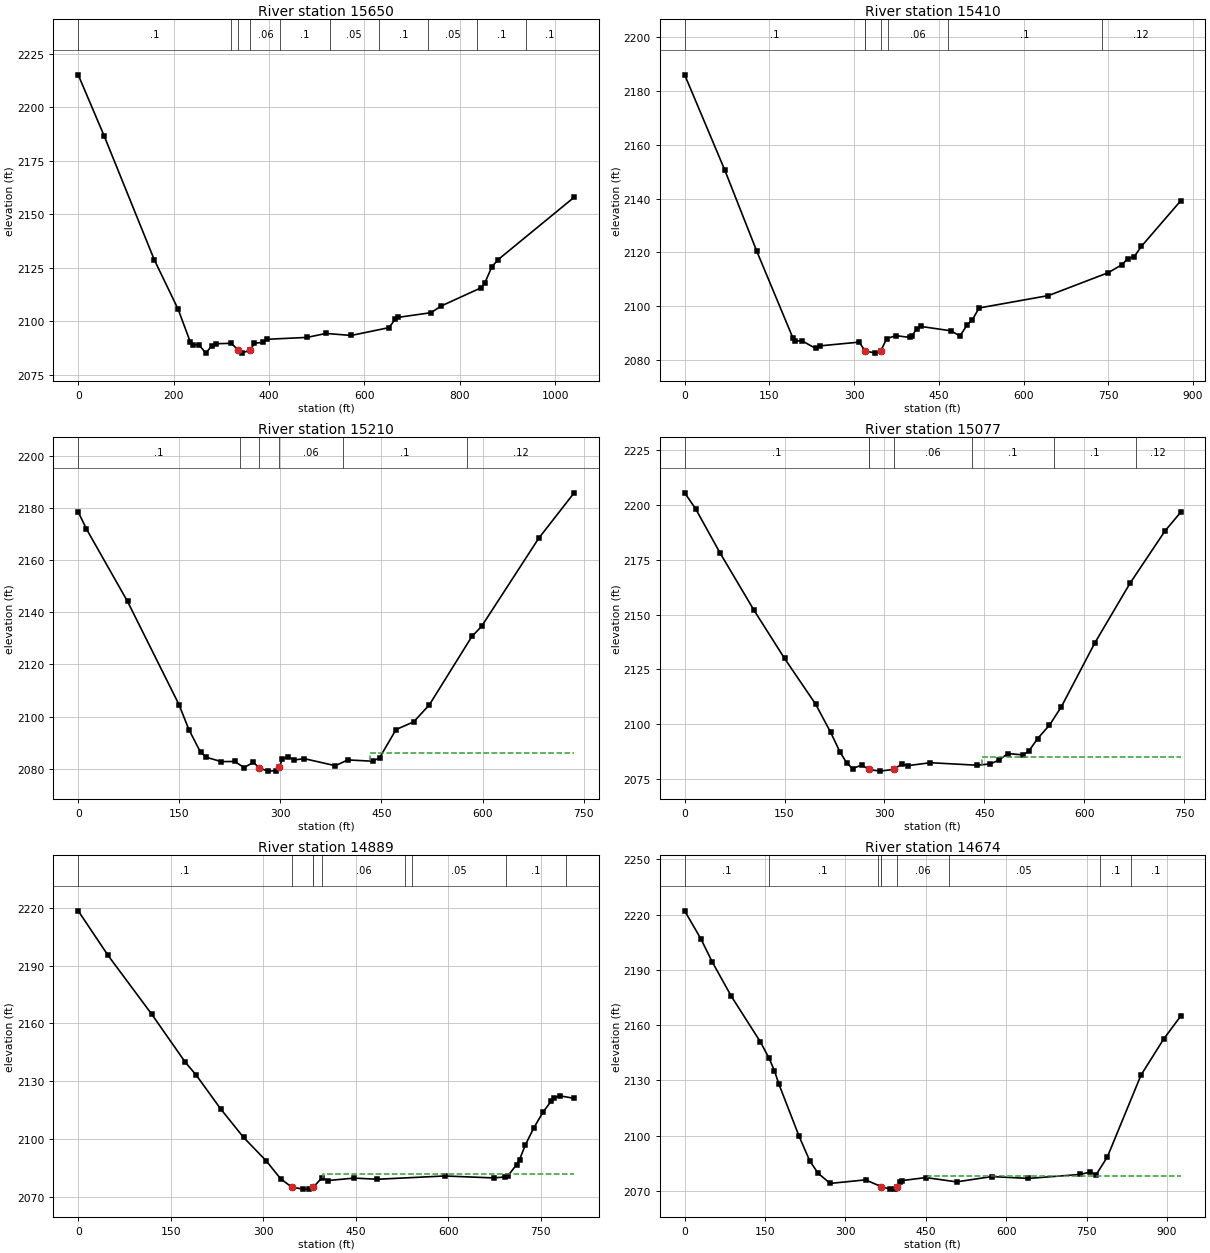
Type RM Length L Ch R = 1 ,15650   ,229,240.9,252
XS GIS Cut Line= 4
2451050.61662214530020.8339351832451248.14675866 529913.91395303
2451461.98672296529812.4305801392451987.52561829529571.407569523
#Sta/Elev= 30
       0 2215.12    54.7 2186.39   159.3 2128.73   209.4 2105.55   234.8 2090.29
   240.8  2088.9   252.9 2088.98   267.3 2085.02   280.6 2088.58   289.5 2089.42
   320.5 2089.61   335.32086.573   342.9 2085.04   360.9 2086.46   369.2 2089.65
   386.9 2090.01   395.7 2091.49   479.7 2092.37   519.4 2094.23   572.2 2093.28
   651.4 2096.94   664.6 2100.91   671.2 2101.76   739.4 2103.92   761.4 2107.11
     845 2115.62   852.2 2117.77     867  2125.4   880.2 2128.74  1039.5 2157.89
#Mann= 10 ,-1 , 0
       0      .1       0  320.16     .06       0   335.3    .045       0
   360.9     .06       0  423.57      .1       0  526.74     .05       0
  629.77      .1       0   732.8     .05       0  835.83      .1       0
  938.86      .1       0
Bank Sta=335.3,360.9
XS Rating Curve= 0 ,0
Exp/Cntr(USF)=0,0
Exp/Cntr=0.3,0.1

Type RM Length L Ch R = 1 ,15410   ,191.4,199.3,206
XS GIS Cut Line= 4
2451112.23152711 530084.261043242451331.50810068530060.702403104
2451547.16026807530096.9464648512451974.84019668530194.805431567
#Sta/Elev= 30
       0 2186.05    70.9 2150.63   127.2  2120.6   191.6 2088.08   195.6 2086.98
   207.7 2087.04   231.9 2084.17     240 2085.15     309 2086.54     3192083.321
   337.4 2082.44   347.22083.341   357.7 2087.84   373.9 2088.96   398.2 2088.28
   402.3 2088.72   410.4 2091.48   418.5 2092.36   471.6 2090.74   487.2 2088.82
   500.3    2093   508.5 2094.61   521.2 2099.25     644 2103.87     750 2112.41
   774.4 2115.42   784.4 2117.65   795.8 2118.37   808.5  2122.2   877.9 2139.12
#Mann= 7 ,-1 , 0
       0      .1       0  318.96    .045       0     319    .045       0
   347.2      .1       0  360.25     .06       0   465.7      .1       0
  738.26     .12       0
Bank Sta=319,347.2
XS Rating Curve= 0 ,0
Exp/Cntr(USF)=0,0
Exp/Cntr=0.3,0.1

Type RM Length L Ch R = 1 ,15210   ,132.4,133.2,131.6
XS GIS Cut Line= 4
2451119.48033946530142.2515420342451295.26403893530216.551868615
 2451471.0477384530321.6596476812451759.18802929530502.879956415
#Sta/Elev= 30
       0 2178.49    12.2 2171.96    73.2 2144.16   149.5 2104.64   164.2 2095.05
   181.6 2086.28   190.3 2084.38   212.6 2082.73   232.2  2082.8   246.2 2080.45
   260.1 2082.48     268 2080.45   281.1 2079.09   292.8 2079.22   298.5 2080.81
     303 2083.63   311.4 2084.64   320.1 2083.33   335.1  2083.9   381.7 2081.16
     400 2083.39   436.9 2082.89   447.3 2084.24   471.7 2095.04   497.9 2097.99
   521.1 2104.51   584.3 2130.76   598.5 2134.56   683.5 2168.42     736 2185.82
#Mann= 6 ,-1 , 0
       0      .1       0  239.56     .06       0     268    .045       0
   298.5     .06       0  392.22      .1       0  576.42     .12       0
#XS Ineff= 2 , 0
                          433.69         2086.03
Permanent Ineff=
       F       F
Bank Sta=268,298.5
XS Rating Curve= 0 ,0
Exp/Cntr(USF)=0,0
Exp/Cntr=0.3,0.1

Type RM Length L Ch R = 1 ,15077   ,183.1,188,187.4
XS GIS Cut Line= 4
2451052.42882523530229.2372902272451220.96371235530325.284053856
2451400.37181799530430.3918329212451706.63413975530584.429095345
#Sta/Elev= 30
       0 2205.58    16.5 2198.26    52.8 2178.31     104 2152.05     150    2130
   196.5  2109.2   219.2 2096.29   233.1 2087.37   243.2 2082.36     252 2079.75
   265.6 2081.35   276.82079.375   292.9 2078.59     3142079.381   325.9 2081.83
   335.1 2081.09   368.9 2082.43   438.6 2081.29   458.3 2081.84   471.7 2083.56
   485.2 2086.62   507.5    2086   516.5  2087.6   529.9 2093.41   547.8 2099.57
   565.8 2108.06   615.6 2136.94   668.7  2164.3   721.4 2188.25   744.7 2196.66
#Mann= 7 ,-1 , 0
       0      .1       0  276.79    .045       0   276.8    .045       0
     314     .06       0  431.76      .1       0  554.38      .1       0
  677.01     .12       0
#XS Ineff= 2 , 0
                          446.81         2084.92
Permanent Ineff=
       F       F
Bank Sta=276.8,314
XS Rating Curve= 0 ,0
Exp/Cntr(USF)=0,0
Exp/Cntr=0.3,0.1

Type RM Length L Ch R = 1 ,14889   ,204.1,214.9,219.3
XS GIS Cut Line= 4
 2450927.3868122530314.4108353322451135.79016724530473.884707017
2451289.82742967530586.2412984322451590.65314216530767.461607166
#Sta/Elev= 30
       0 2218.42    48.4 2195.25   119.3 2164.67   173.9 2139.65   191.1  2133.2
     231 2115.53   268.1 2100.73   304.9 2088.55   328.2 2079.24   346.42074.878
   365.1 2073.85     375 2073.86   381.52074.865   394.8 2079.64   405.5 2078.33
   447.4 2079.58   485.3 2078.98   594.2 2080.68   673.6 2079.68   692.3 2080.17
     697 2080.79     711  2086.6   715.7 2089.17   725.2 2096.83     739 2105.77
   754.4 2114.11     767 2119.52   771.9 2121.15     781 2122.32   804.3 2121.02
#Mann= 9 ,-1 , 0
       0      .1       0   346.4    .045       0   381.5      .1       0
  381.52      .1       0  395.35     .06       0  530.31      .1       0
  541.56     .05       0  693.62      .1       0  790.66      .1       0
#XS Ineff= 1 ,-1
   396.6804.2734 2081.51
Permanent Ineff=
       F
Bank Sta=346.4,381.5
XS Rating Curve= 0 ,0
Exp/Cntr(USF)=0,0
Exp/Cntr=0.3,0.1

Type RM Length L Ch R = 1 ,14674   ,274.3,278.6,276.7
XS GIS Cut Line= 4
2450822.27903313530386.8989588252451025.24577892 530607.98773548
2451161.16101047   530805.5178722451411.24503652531099.094772149
#Sta/Elev= 30
       0 2222.04    30.3 2206.78    51.3 2194.39    86.9 2175.74   141.2 2150.96
   157.5 2142.06   167.4 2135.34   175.8 2128.01   213.6 2099.64   233.5  2086.3
   249.1 2079.59   271.5  2074.1   337.6 2076.03   366.72072.375   383.8    2071
   392.5 2071.22   396.32072.398   401.1    2075   405.6 2075.63     450 2077.27
   507.6 2074.94   573.2 2077.81   641.5 2076.82   737.8 2078.95   757.1  2080.3
   767.6  2078.7   788.9 2088.48   851.7  2132.9   893.9 2152.42   925.6 2164.85
#Mann= 9 ,-1 , 0
       0      .1       0  156.83      .1       0  360.02     .06       0
  366.68     .06       0   366.7    .045       0   396.3     .06       0
  492.56     .05       0  774.74      .1       0  833.32      .1       0
#XS Ineff= 1 ,-1
  454.49925.5538 2078.09
Permanent Ineff=
       F
Bank Sta=366.7,396.3
XS Rating Curve= 0 ,0
Exp/Cntr(USF)=0,0
Exp/Cntr=0.3,0.1

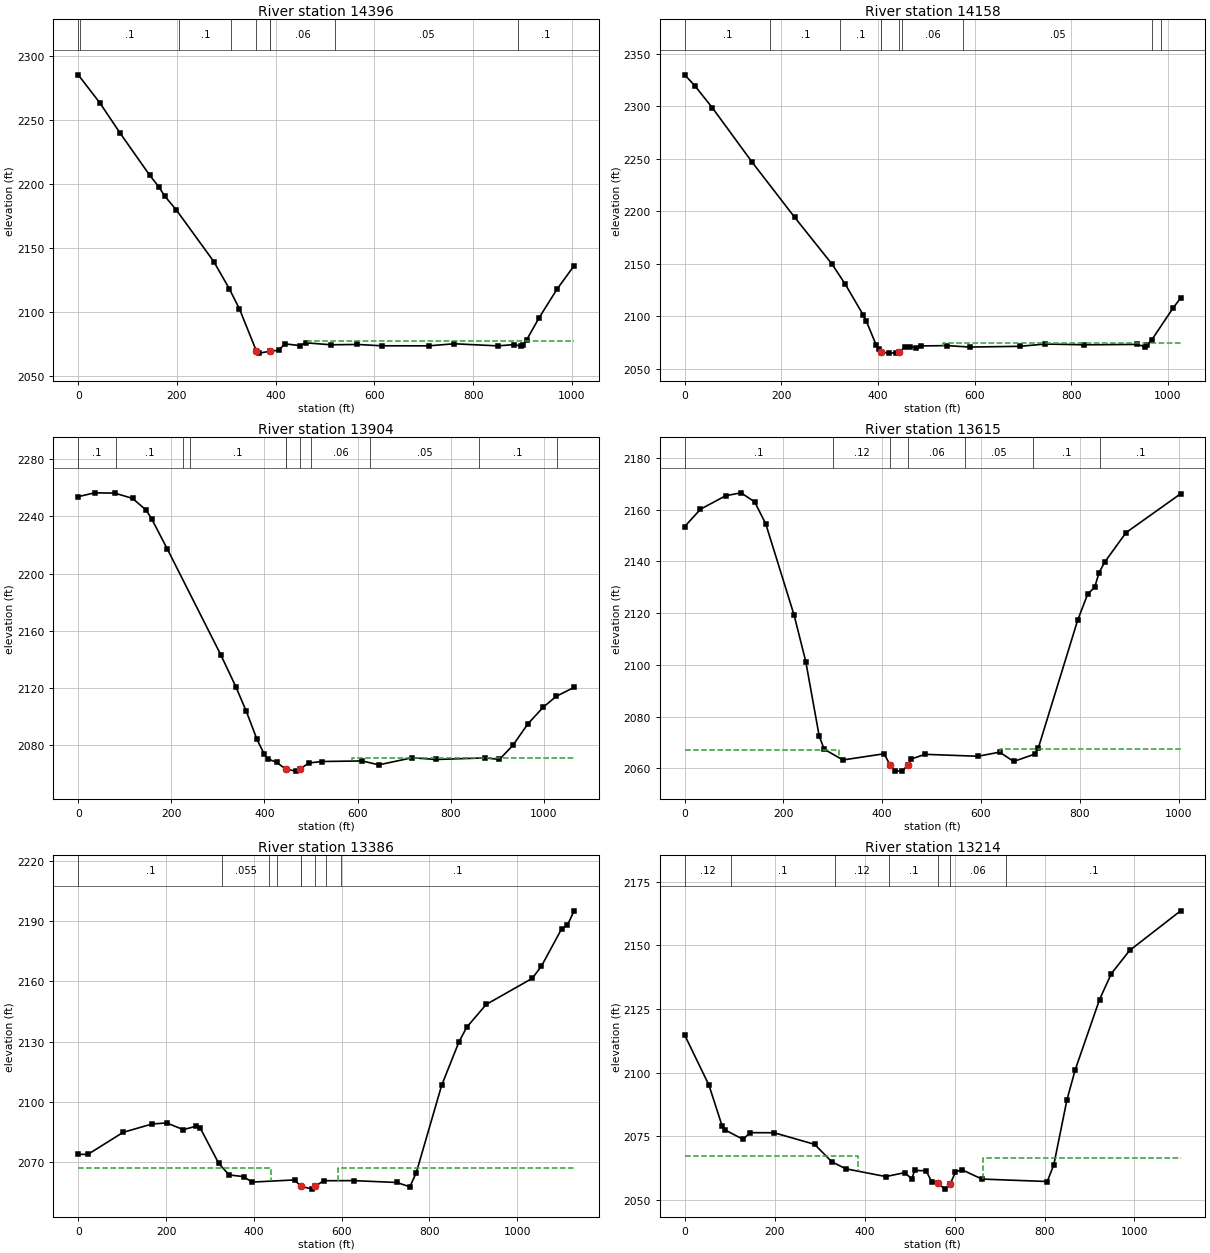
Type RM Length L Ch R = 1 ,14396   ,244.1,237.3,222.5
XS GIS Cut Line= 4
2450622.93669353530457.5748792312450753.41531581 530669.60264045
2450887.51834428530890.6914171052451246.33455557531235.010003699
#Sta/Elev= 30
       0  2285.1    43.8 2263.21    85.1 2239.46   144.6 2206.83   163.4 2197.58
   175.3  2190.4   198.8  2179.6   274.7 2139.26   306.2 2117.98   326.6 2102.35
   361.12069.314   367.2 2067.79   389.1 2069.31   405.8 2070.01   418.9 2075.01
   448.9 2073.71     461 2075.84     512  2074.3   565.6 2074.55   614.6 2073.53
     710 2073.48     762 2075.09   850.2 2073.45   883.4 2074.47   897.5 2073.16
   900.4 2073.84   908.9 2078.33   933.3  2095.1     970 2117.67  1004.8 2136.09
#Mann= 9 ,-1 , 0
       0      .1       0    3.65      .1       0  204.68      .1       0
  310.29     .06       0   361.1    .045       0   389.1     .06       0
  389.11     .06       0  521.15     .05       0  891.58      .1       0
#XS Ineff= 2 , 0
                          465.35         2077.01
Permanent Ineff=
       F       F
Bank Sta=361.1,389.1
XS Rating Curve= 0 ,0
Exp/Cntr(USF)=0,0
Exp/Cntr=0.3,0.1

Type RM Length L Ch R = 1 ,14158   ,249.6,254,249.6
XS GIS Cut Line= 4
2450345.66962116530714.9077176332450574.00721017530901.564635629
2450807.78140843531032.0432579172451191.96846295531291.188299407
#Sta/Elev= 30
       0 2329.73    20.7 2319.52    56.9 2298.61     140 2246.42   227.5  2194.3
   305.3 2149.51   332.4 2130.56   369.1 2101.67   375.8 2095.54   396.5 2072.59
   401.1 2068.65   406.72066.281   422.9 2065.16   437.8 2065.48   443.6  2066.3
   456.1  2070.8   465.3 2071.19     479 2070.31   488.2 2072.01   543.1 2072.29
   589.9 2070.94   693.6 2071.63   745.5  2073.8   826.2 2073.09   935.6 2073.44
   952.2 2071.33     957 2072.86   966.7 2077.99  1011.2 2108.51  1026.1 2117.44
#Mann= 10 ,-1 , 0
       0      .1       0  177.45      .1       0  322.27      .1       0
  406.65      .1       0   406.7    .045       0   443.6      .1       0
  448.96     .06       0  576.64     .05       0   967.7      .1       0
  985.45      .1       0
#XS Ineff= 1 ,-1
  534.541026.061  2074.5
Permanent Ineff=
       F
Bank Sta=406.7,443.6
XS Rating Curve= 0 ,0
Exp/Cntr(USF)=0,0
Exp/Cntr=0.3,0.1

Type RM Length L Ch R = 1 ,13904   ,287,289.2,290.6
XS GIS Cut Line= 4
 2450226.0642174530950.494118987 2450483.3970558531124.465615371
2450717.17125407531260.3808469222451150.28779194531476.033014315
#Sta/Elev= 30
       0 2253.81    35.3 2256.49    78.6 2256.29   116.7 2252.59   145.7 2244.47
   157.8 2238.24   190.9 2217.52   306.1 2143.32   338.3 2121.11   360.8 2103.94
   383.9 2084.17   399.7 2073.75     407 2070.67     426 2068.15   445.22063.559
     467 2062.03   476.92063.579   494.9  2067.7   522.6 2068.75   609.6 2069.15
   645.4 2066.41   716.8 2071.36     769 2070.17   873.2 2071.26   904.5 2070.22
   933.1 2079.95   965.9 2095.19   998.7 2106.76  1026.4 2114.28  1064.9 2120.59
#Mann= 11 ,-1 , 0
       0      .1       0   80.99      .1       0  224.29     .12       0
   239.1      .1       0  445.15      .1       0   445.2    .045       0
   476.9      .1       0  500.24     .06       0  626.43     .05       0
  859.95      .1       0 1028.73      .1       0
#XS Ineff= 1 ,-1
  587.45 1064.87 2071.36
Permanent Ineff=
       F
Bank Sta=445.2,476.9
XS Rating Curve= 0 ,0
Exp/Cntr(USF)=0,0
Exp/Cntr=0.3,0.1

Type RM Length L Ch R = 1 ,13615   ,224.8,228.9,229
XS GIS Cut Line= 4
2450166.26151552 531166.146286382450407.28452613531405.357093909
2450651.93194292531568.4553717692450958.19426468531776.858726813
#Sta/Elev= 30
       0 2153.46      32 2160.17    82.9 2165.38     114 2166.51   141.6 2163.03
   164.1 2154.54   221.5 2119.24   245.2 2101.24   272.4 2072.39   282.5 2067.33
   320.5  2063.2   403.8 2065.59   415.8 2061.26   425.5 2058.96   439.9 2058.88
   452.82061.368   459.1 2063.58   486.6 2065.38   593.7 2064.63   637.9 2066.22
     666 2062.61   709.4 2065.51   716.1 2067.89   795.7 2117.28     816 2127.38
   830.3 2130.04   838.9 2135.62   850.4 2139.72   893.6 2151.12  1004.1 2166.14
#Mann= 7 ,-1 , 0
       0      .1       0  299.75     .12       0   415.8    .045       0
   452.8     .06       0  568.01     .05       0  704.22      .1       0
  841.01      .1       0
#XS Ineff= 2 ,-1
       0  312.72 2067.09  638.331004.052 2067.61
Permanent Ineff=
       F       F
Bank Sta=415.8,452.8
XS Rating Curve= 0 ,0
Exp/Cntr(USF)=0,0
Exp/Cntr=0.3,0.1

Type RM Length L Ch R = 1 ,13386   ,171,171.6,171.2
XS GIS Cut Line= 4
2450062.96593954   531220.5123792450300.36454398531595.638418079
2450496.08247741531749.6756805032450851.27428253 532003.38411273
#Sta/Elev= 30
       0 2073.98      22 2073.94   102.2 2084.91   168.5 2089.09   201.6 2089.59
   239.3 2086.26   268.9 2087.99   277.4 2087.29     320 2069.48   343.6 2063.72
   376.8 2062.89   395.7 2060.16   492.8 2061.24   506.82058.065   533.3 2056.66
   539.82058.047   558.9 2060.84   627.4 2060.89   725.8 2059.96   755.3 2057.81
     770 2064.88   827.7 2108.28   867.1 2129.91     885 2137.26   929.1 2148.53
  1034.1 2161.54  1055.1 2167.66  1101.1 2186.21  1114.1    2188  1129.5 2195.14
#Mann= 9 ,-1 , 0
       0      .1       0  328.18    .055       0  434.53     .12       0
  451.88     .06       0  506.78     .06       0   506.8    .045       0
   539.8     .06       0  565.42    .055       0  598.65      .1       0
#XS Ineff= 2 ,-1
       0  439.21 2067.01  592.561129.495  2067.3
Permanent Ineff=
       F       F
Bank Sta=506.8,539.8
XS Rating Curve= 0 ,0
Exp/Cntr(USF)=0,0
Exp/Cntr=0.3,0.1

Type RM Length L Ch R = 1 ,13214   ,130,128.3,125.7
XS GIS Cut Line= 4
2449867.24800611531369.113032162 2450126.3930476531666.314338485
 2450354.7306366 531860.220068832450689.98820776532093.994267097
#Sta/Elev= 30
       0 2114.77      54  2095.1    83.1 2079.18    90.5 2077.47   129.7 2073.87
   145.5 2076.48   198.7 2076.45   288.9 2071.89   326.9 2065.09   357.9 2062.32
   447.3 2059.25   489.2  2060.8     505 2058.32   511.3 2061.69   536.9  2061.5
   549.7 2056.99   562.1 2056.64   579.4 2054.33   590.8 2056.51   602.1 2061.07
   616.3 2061.94   660.9 2058.27   806.1 2057.32   820.7  2063.9   849.9 2089.39
   868.2 2101.11   922.3 2128.68   948.6 2138.88   989.3 2147.96  1102.6  2163.5
#Mann= 7 ,-1 , 0
       0     .12       0  102.45      .1       0   333.1     .12       0
   454.8      .1       0   562.1    .045       0   590.8     .06       0
  714.36      .1       0
#XS Ineff= 2 ,-1
       0  384.62 2067.26  664.021102.593 2066.68
Permanent Ineff=
       F       F
Bank Sta=562.1,590.8
XS Rating Curve= 0 ,0
Exp/Cntr(USF)=0,0
Exp/Cntr=0.5,0.3