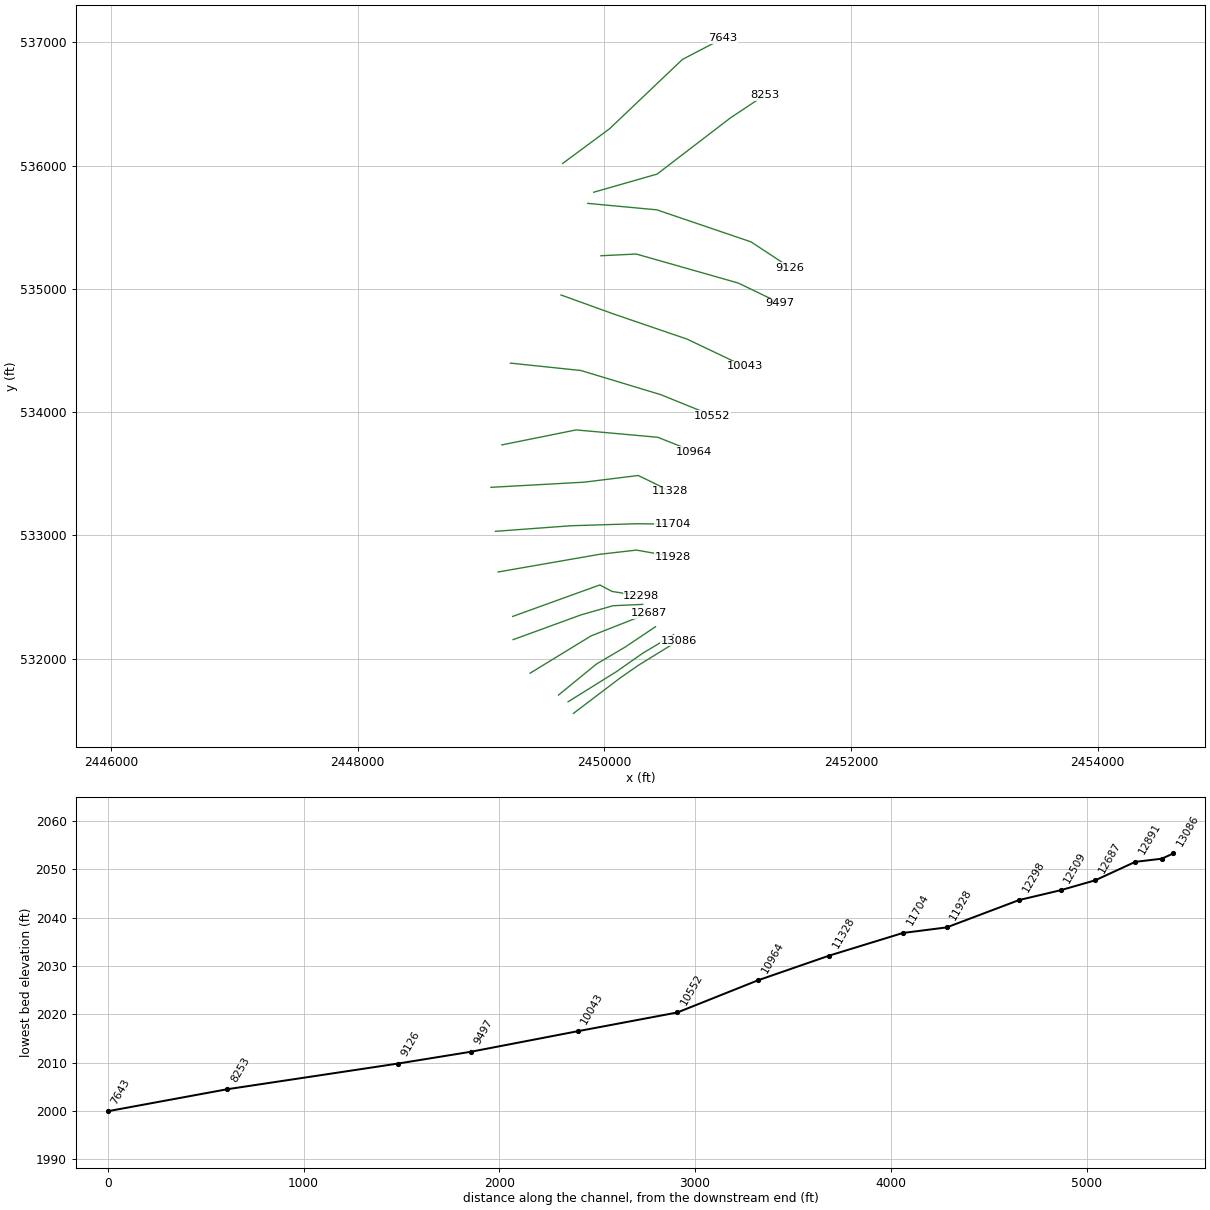
HEC-RAS study BRUSHFK.prj: BRUSHFK

--- BRUSHFK.g01 (geometry) --- (continued)

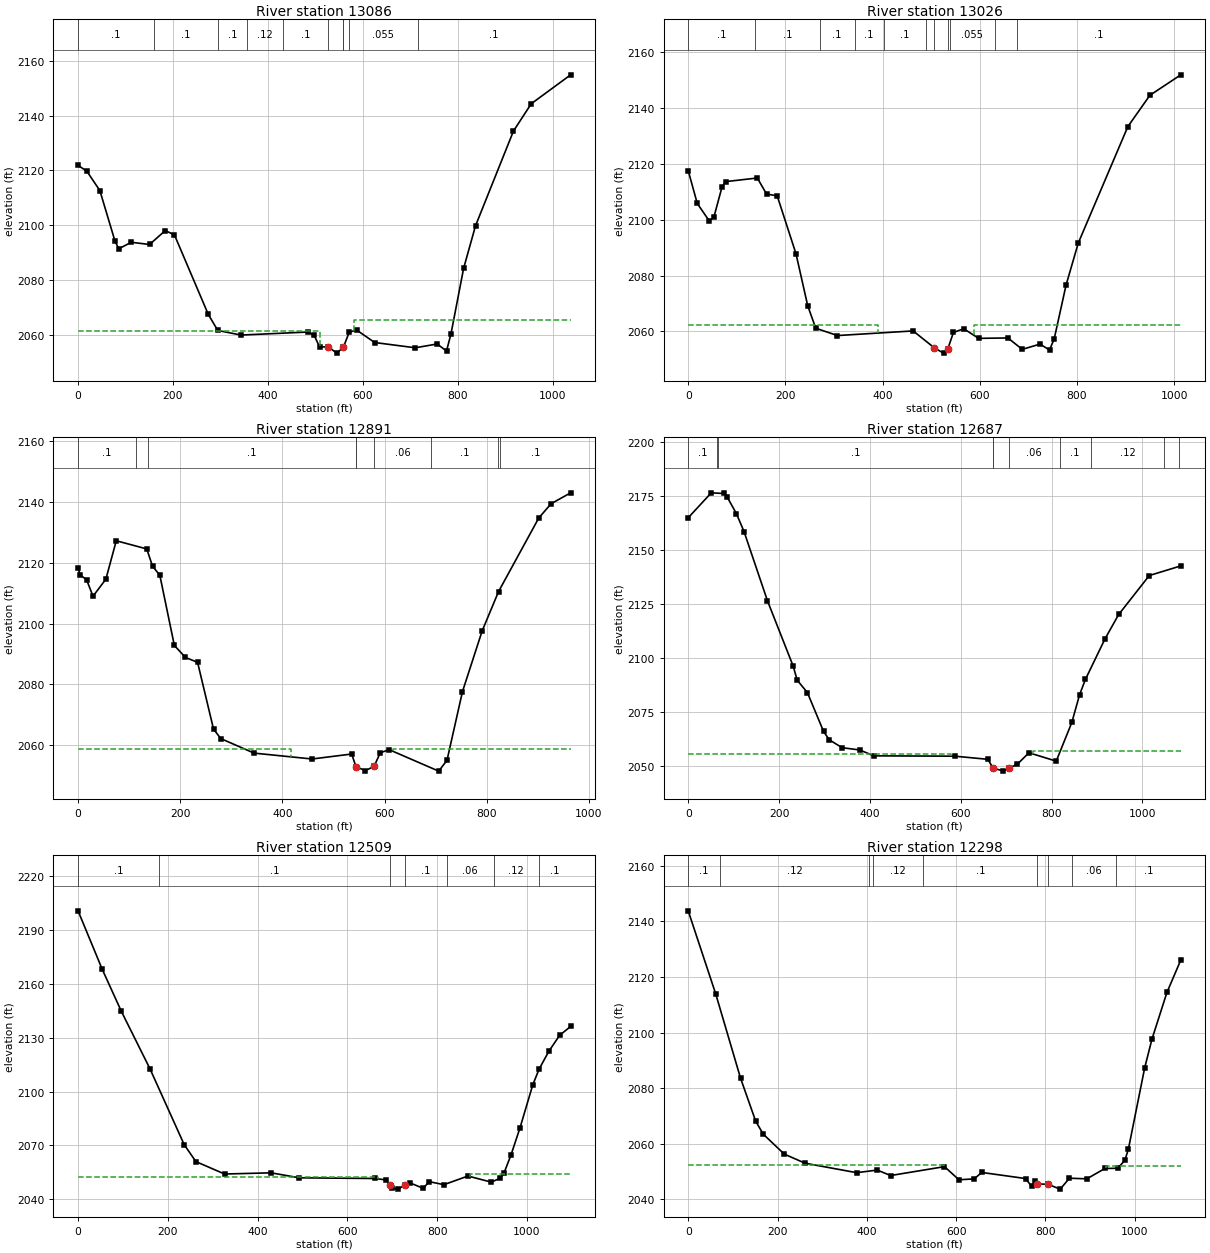
Type RM Length L Ch R = 1 ,13086   ,59.7,60.1,60.3
XS GIS Cut Line= 4
2449749.45480543531555.769950158 2450126.3930476531842.098037957
2450274.99370076531945.3936139352450601.19025648 532146.54815663
#Sta/Elev= 30
       0  2121.8    18.4 2119.73      46 2112.61    77.9 2094.14    85.9  2091.4
   112.1 2093.77   150.6 2092.96   183.7 2098.03     203 2096.48   274.3 2067.47
   294.3  2061.6   343.2 2059.92   483.5 2061.02   497.2 2059.88   508.7  2055.6
   527.4  2055.6   544.8 2053.33   558.92055.455   571.2 2060.98   586.9 2061.75
   624.8  2057.2   710.4 2055.28   756.3 2056.66   776.2 2054.12   785.6 2060.39
   812.2 2084.28   837.3 2099.81   917.2 2134.35   954.6  2144.3  1037.6 2154.85
#Mann= 10 ,-1 , 0
       0      .1       0  160.18      .1       0  295.64      .1       0
  355.26     .12       0  431.11      .1       0   527.4    .045       0
   558.9      .1       0  558.92      .1       0  570.61    .055       0
  715.56      .1       0
#XS Ineff= 2 ,-1
       0     510 2061.39  580.651037.565 2065.26
Permanent Ineff=
       F       F
Bank Sta=527.4,558.9
XS Rating Curve= 0 ,0
Exp/Cntr(USF)=0,0
Exp/Cntr=0.5,0.3

Type RM Length L Ch R = 1 ,13026   ,135.5,134.9,132.8
XS GIS Cut Line= 4
2449705.96193133531650.0045106992450095.58559511531892.839724403
2450313.04996559532045.0647837392450561.32178856532193.665436901
#Sta/Elev= 30
       0  2117.6    18.6 2105.84    43.3 2099.58    52.8 2100.87    69.7 2111.78
    77.3 2113.64   142.3 2114.93   161.2  2109.2   183.2 2108.54   221.9 2087.79
     246 2069.19   262.5 2061.15   307.3 2058.52     463 2060.18   506.9 2054.08
   525.5 2052.23   534.6 2053.88     546 2059.65   567.3 2060.95   597.8 2057.52
   658.1 2057.66   687.6 2053.58   724.2 2055.46   743.7 2053.35   753.4 2057.37
   777.8 2076.62   802.9 2091.65     905 2133.35   950.3 2144.54  1013.9 2151.87
#Mann= 11 ,-1 , 0
       0      .1       0  138.41      .1       0   270.3      .1       0
  342.96      .1       0  402.18      .1       0  490.44      .1       0
   506.9    .045       0   534.6      .1       0  537.85    .055       0
  631.29     .06       0  676.39      .1       0
#XS Ineff= 2 ,-1
       0  390.12 2062.36  587.651013.898 2062.36
Permanent Ineff=
       F       F
Bank Sta=506.9,534.6
XS Rating Curve= 0 ,0
Exp/Cntr(USF)=0,0
Exp/Cntr=0.5,0.3

Type RM Length L Ch R = 1 ,12891   ,207.2,204.5,200.4
XS GIS Cut Line= 4
2449628.03719858531704.3706033192449936.11172342531956.266832459
2450166.26151552 532092.182064012450414.53333848532258.904748045
#Sta/Elev= 30
       0 2118.32       4 2115.92    16.6 2114.39    29.3 2108.94    54.5 2114.55
    74.8 2127.14   134.5 2124.46   145.8  2118.8   160.1 2115.83   188.5 2092.81
   210.2 2088.87     234 2087.27   265.2 2065.37   279.5 2062.25   344.5 2057.49
   458.2 2055.56   535.7 2057.19   544.12053.012   562.4 2051.75   579.5 2053.12
   591.6 2057.61   609.2 2058.61     706 2051.58   722.3 2055.14   752.5 2077.64
   791.1 2097.58   823.2 2110.48   901.9  2134.6     926 2139.28   964.3 2142.86
#Mann= 9 ,-1 , 0
       0      .1       0  113.72      .1       0  136.58      .1       0
  544.06      .1       0   544.1    .045       0   579.5     .06       0
   690.7      .1       0  822.16     .12       0   826.7      .1       0
#XS Ineff= 2 ,-1
       0  416.94 2058.96  616.17964.2903 2058.69
Permanent Ineff=
       F       F
Bank Sta=544.1,579.5
XS Rating Curve= 0 ,0
Exp/Cntr(USF)=0,0
Exp/Cntr=0.3,0.1

Type RM Length L Ch R = 1 ,12687   ,179.3,177.4,175.2
XS GIS Cut Line= 4
2449397.88740649531881.9665058792449892.61884933532184.604421464
2450099.21000129532266.1535603942450361.97944895532369.449136372
#Sta/Elev= 30
       0    2165    50.8 2176.55    78.4 2176.25    85.7 2174.65     106 2166.98
   122.9 2158.64   174.5 2126.59   230.8 2096.52   240.1 2089.81   262.4 2084.11
     298 2066.13   310.5 2062.25     339  2058.6   377.4 2057.56     409 2054.83
   586.8 2054.68   659.6 2053.23   671.22049.202   694.1 2047.76   706.22049.211
   724.2 2050.89   750.2 2056.26   810.2 2052.38   844.5 2070.27   861.7 2083.18
   874.6 2090.28   917.6 2108.98   947.7 2120.25  1015.1 2138.28  1084.4 2142.73
#Mann= 10 ,-1 , 0
       0      .1       0   63.53      .1       0   64.95      .1       0
  671.18      .1       0   671.2    .045       0   706.2     .06       0
  817.54      .1       0  886.03     .12       0 1048.48      .1       0
  1079.4     .12       0
#XS Ineff= 2 , 0
          579.31 2055.65  758.39         2057.06
Permanent Ineff=
       F       F
Bank Sta=671.2,706.2
XS Rating Curve= 0 ,0
Exp/Cntr(USF)=0,0
Exp/Cntr=0.3,0.1

Type RM Length L Ch R = 1 ,12509   ,228.3,211.7,196.7
XS GIS Cut Line= 4
2449260.15997185532153.796968979 2449811.0697104532354.951511674
2450070.21475189532429.251838255 2450311.2377625532440.125056779
#Sta/Elev= 30
       0 2200.61    53.9 2168.04    96.4 2144.69   160.3 2112.64   236.4 2070.48
   262.5 2061.03   326.4 2054.11   430.2 2054.77   492.6    2052   660.6 2051.62
     686 2050.86     6952047.814   699.4 2046.25   712.3  2045.7   728.5  2047.9
   740.1 2049.11   769.2 2046.11   781.7 2049.89     815 2048.18   868.6 2052.99
   920.7 2049.59   940.7 2051.82   948.7 2054.55   964.7  2064.9   984.6 2079.89
  1012.8 2103.62  1026.8 2112.38  1048.8 2122.45  1072.8  2131.3  1097.3 2136.27
#Mann= 7 ,-1 , 0
       0      .1       0   180.3      .1       0     695    .045       0
   728.5      .1       0   821.5     .06       0  925.58     .12       0
 1027.04      .1       0
#XS Ineff= 2 , 0
          668.17 2052.66  873.71         2054.25
Permanent Ineff=
       F       F
Bank Sta=695,728.5
XS Rating Curve= 0 ,0
Exp/Cntr(USF)=0,0
Exp/Cntr=0.3,0.1

Type RM Length L Ch R = 1 ,12298   ,351.4,369.6,380.7
XS GIS Cut Line= 4
2449256.53556567532342.2660900622449963.29476974532597.786725377
2450061.15373645532545.2328358442450298.55234089 532507.17657101
#Sta/Elev= 30
       0 2143.78    61.9 2113.76   117.2 2083.59   151.2 2068.08   168.2 2063.42
     215 2056.28   261.8 2052.99   377.1 2049.59   423.4 2050.52   453.2 2048.56
   573.9 2051.76   606.3 2047.03   640.4 2047.36   657.4 2049.67   755.4 2047.48
   769.1 2044.65   776.9  2046.6   781.62045.538   805.4 2045.41     833 2043.67
   853.7  2047.6   892.6 2047.37   933.1  2051.1   961.4 2051.17   977.7 2053.97
   985.8 2058.14  1022.2 2087.33  1038.4  2097.6    1072 2114.43    1103 2126.08
#Mann= 9 ,-1 , 0
       0      .1       0   71.82     .12       0   403.9      .1       0
  412.77     .12       0  526.43      .1       0   781.6    .045       0
   805.4      .1       0  858.62     .06       0  958.16      .1       0
#XS Ineff= 2 , 0
          573.88 2052.51  936.12         2051.91
Permanent Ineff=
       F       F
Bank Sta=781.6,805.4
XS Rating Curve= 0 ,0
Exp/Cntr(USF)=0,0
Exp/Cntr=0.3,0.1

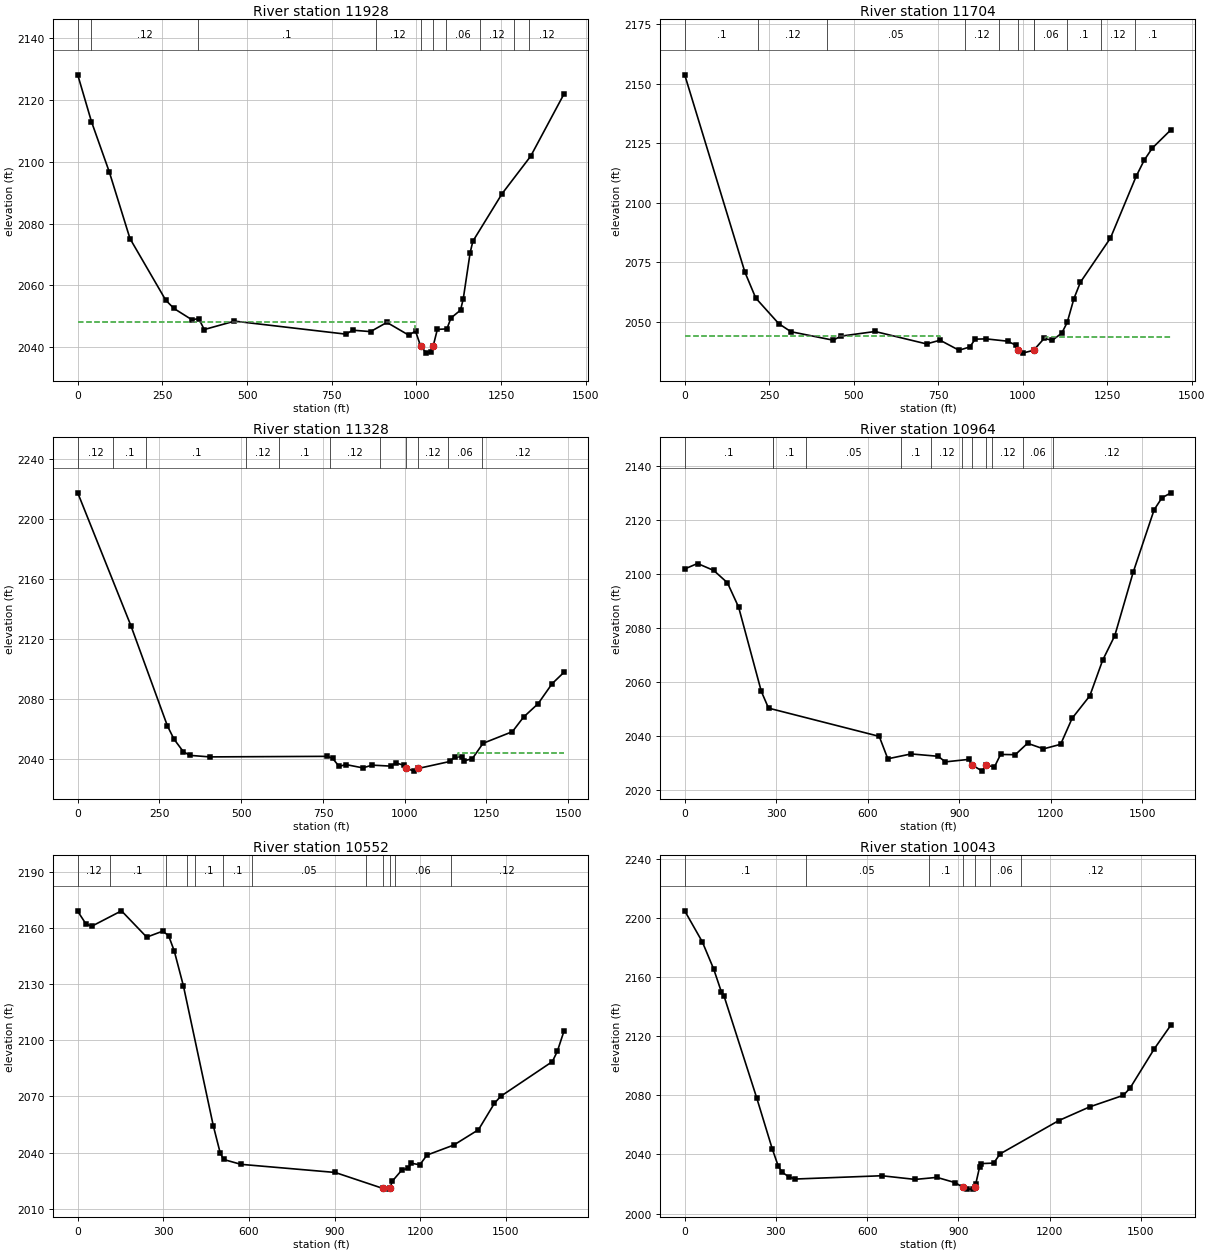
Type RM Length L Ch R = 1 ,11928   ,226.5,224.1,221.6
XS GIS Cut Line= 4
  2449138.742365532702.8945044422449959.67036356532846.058548342
2450260.49607606532880.4904070022450555.88517929532827.936517469
#Sta/Elev= 30
       0 2128.16    40.6 2112.98    93.5 2096.61   154.3 2075.11   259.9 2055.16
   284.2 2052.47     337 2048.83   357.3 2049.19   373.6 2045.65   462.9 2048.37
   791.8 2044.16   812.1 2045.44   864.6 2044.98   912.9 2047.96   977.3 2043.84
   997.5 2045.14  1012.22040.375  1029.7 2038.01  1041.7 2038.42  1049.8 2040.39
  1061.9  2045.7  1090.1 2045.86  1102.1 2049.38  1130.3 2051.94  1138.4 2055.57
  1158.7 2070.51  1166.8 2074.26  1253.2 2089.68  1337.5  2101.8  1436.1    2122
#Mann= 10 ,-1 , 0
       0      .1       0   40.34     .12       0  355.66      .1       0
  880.32     .12       0  1012.2    .045       0  1049.8     .12       0
  1086.7     .06       0 1187.87     .12       0  1287.2      .1       0
 1332.05     .12       0
#XS Ineff= 2 , 0
          996.72 2048.19
Permanent Ineff=
       F       F
Bank Sta=1012.2,1049.8
XS Rating Curve= 0 ,0
Exp/Cntr(USF)=0,0
Exp/Cntr=0.3,0.1

Type RM Length L Ch R = 1 ,11704   ,372.7,375.6,377.3
XS GIS Cut Line= 4
2449116.99592795533032.7154663382449729.52057147533078.020543521
2450262.30827915533094.3303713072450554.07297621533090.705965133
#Sta/Elev= 30
       0 2153.81   178.2 2070.84   210.3 2059.97   278.5  2049.2   314.6 2045.84
   438.9  2042.3     463    2044   563.3 2045.94   715.5 2040.72   755.5 2042.28
   811.5 2038.07   843.5 2039.43   859.5 2042.72   891.6 2042.84   955.6 2041.86
   979.6  2040.2   987.6 2038.31   999.6 2036.85  1032.4 2038.05  1063.6 2043.04
  1087.6 2042.22  1115.7 2045.27  1131.7 2049.73  1151.7 2059.79  1170.8 2066.64
  1259.7  2085.2  1335.7 2111.12  1359.7 2117.97  1383.7 2123.04    1439 2130.76
#Mann= 11 ,-1 , 0
       0      .1       0  217.66     .12       0  421.89     .05       0
  828.34     .12       0   929.5      .1       0   987.6    .045       0
  1032.4     .06       0 1032.44     .06       0 1131.83      .1       0
 1232.37     .12       0 1332.79      .1       0
#XS Ineff= 2 , 0
           755.5 2043.92 1066.37         2043.74
Permanent Ineff=
       F       F
Bank Sta=987.6,1032.4
XS Rating Curve= 0 ,0
Exp/Cntr(USF)=0,0
Exp/Cntr=0.3,0.1

Type RM Length L Ch R = 1 ,11328   ,369.5,363.9,359.4
XS GIS Cut Line= 4
 2449080.7518662533389.7194745432449836.44055362533431.400145552
2450274.99370076533485.7662381722450534.13874225533358.912022059
#Sta/Elev= 30
       0 2217.41   162.5 2129.03   274.4 2062.19   294.4 2053.46   322.5 2045.23
   342.5 2042.67   403.7 2041.64   763.2 2042.01   779.3 2040.71   799.5 2035.27
   819.6 2036.55     872 2034.33   900.2 2036.16   956.7 2035.51   972.8 2037.57
     997 2036.17  1003.9 2034.05  1029.2 2032.17  1041.3 2033.95    1138 2038.59
  1154.2 2041.82  1174.2 2041.45  1182.4 2039.07  1206.7 2040.46  1239.6  2050.7
  1329.3 2058.44  1363.3 2068.11  1407.8 2077.04  1450.9 2090.41  1487.3 2098.01
#Mann= 11 ,-1 , 0
       0     .12       0   108.5      .1       0  210.18      .1       0
  515.21     .12       0  616.89      .1       0  771.52     .12       0
  924.83      .1       0  1003.9    .045       0  1041.3     .12       0
 1131.76     .06       0 1235.33     .12       0
#XS Ineff= 1 ,-1
 1163.141487.275 2043.97
Permanent Ineff=
       F
Bank Sta=1003.9,1041.3
XS Rating Curve= 0 ,0
Exp/Cntr(USF)=0,0
Exp/Cntr=0.3,0.1

Type RM Length L Ch R = 1 ,10964   ,418.4,412.3,404.5
XS GIS Cut Line= 4
2449169.54981748533734.0380611382449771.20124248533855.455667989
2450432.65536936533795.652966107 2450726.2322695533679.671968518
#Sta/Elev= 30
       0 2101.98      42    2104    95.1 2101.43     140 2096.86   176.7 2087.81
   250.9 2056.64   274.6 2050.41   637.4 2039.94   665.5 2031.63   741.8 2033.43
   830.2 2032.56   854.3 2030.49   930.6 2031.41   941.7 2029.34   974.8 2027.06
   985.9  2029.3    1015 2028.62    1035 2033.24  1083.2 2033.15  1123.4 2037.38
  1175.6 2035.31  1231.8 2036.99  1269.5 2046.64  1327.5 2054.98  1369.5 2068.16
  1409.2 2077.25  1469.4 2100.71  1538.2 2123.92    1564 2128.37  1593.6 2130.19
#Mann= 12 ,-1 , 0
       0      .1       0  288.79     .12       0   290.7      .1       0
  396.82     .05       0  708.91      .1       0  808.48     .12       0
  908.04      .1       0   941.7    .045       0   985.9      .1       0
 1007.61     .12       0 1107.18     .06       0 1206.74     .12       0
Bank Sta=941.7,985.9
XS Rating Curve= 0 ,0
Exp/Cntr(USF)=0,0
Exp/Cntr=0.3,0.1

Type RM Length L Ch R = 1 ,10552   ,507.2,508.9,507.9
XS GIS Cut Line= 4
 2449238.4135348534397.3043911032449809.25750731534337.501689221
2450456.21400949534141.7837557892450876.64512575533971.436665579
#Sta/Elev= 30
       0 2169.13    28.5 2162.45    48.6 2161.12   153.2 2169.41   241.6 2155.32
   297.4  2158.5   318.1 2156.19   338.2 2147.85   370.2 2129.18   474.9 2054.29
     499 2039.79   511.1 2036.26   571.4 2033.67   901.5 2029.32  1068.1 2020.81
  1089.5 2020.39  1093.6 2020.85  1102.1 2024.69  1135.5 2030.66  1156.4 2031.52
  1168.9 2034.25  1198.2 2033.41  1223.3 2038.62  1317.3    2044  1403.7  2052.2
  1459.8 2066.41  1481.3 2070.06  1662.4 2088.67  1679.9 2094.17  1703.5 2105.15
#Mann= 12 ,-1 , 0
       0     .12       0  111.81      .1       0  310.76     .12       0
   383.9      .1       0  410.24      .1       0  509.72      .1       0
  609.45     .05       0 1010.26      .1       0  1068.1    .045       0
  1093.6      .1       0 1110.46     .06       0 1306.09     .12       0
Bank Sta=1068.1,1093.6
XS Rating Curve= 0 ,0
Exp/Cntr(USF)=0,0
Exp/Cntr=0.3,0.1

Type RM Length L Ch R = 1 ,10043   ,545.8,546.5,547.7
XS GIS Cut Line= 4
2449648.17278844 534950.227688642450077.06085244534795.183646723
2450671.06075329534591.8141891442451136.19287904534370.322700692
#Sta/Elev= 30
       0 2204.92      58 2183.86    95.2 2165.54   120.2 2150.25   129.6 2147.03
   236.7 2078.31   287.7 2043.87   307.6 2032.07   320.1 2028.01     343 2024.71
   363.9 2023.35   648.1 2025.57     758 2023.08   829.3 2024.46   889.2  2020.9
   914.5 2017.77   926.9 2016.51   948.3 2016.59   953.3 2017.83   956.7 2019.77
   969.4 2031.33   975.6  2033.8  1015.9 2034.14  1037.1 2040.38  1229.8 2062.91
  1331.7 2072.21  1442.4 2080.03  1464.6    2085  1544.3 2111.59  1599.1 2127.72
#Mann= 7 ,-1 , 0
       0      .1       0  398.45     .05       0  801.65      .1       0
   914.5    .045       0   953.3      .1       0 1003.16     .06       0
 1104.45     .12       0
Bank Sta=914.5,953.3
XS Rating Curve= 0 ,0
Exp/Cntr(USF)=0,0
Exp/Cntr=0.3,0.1

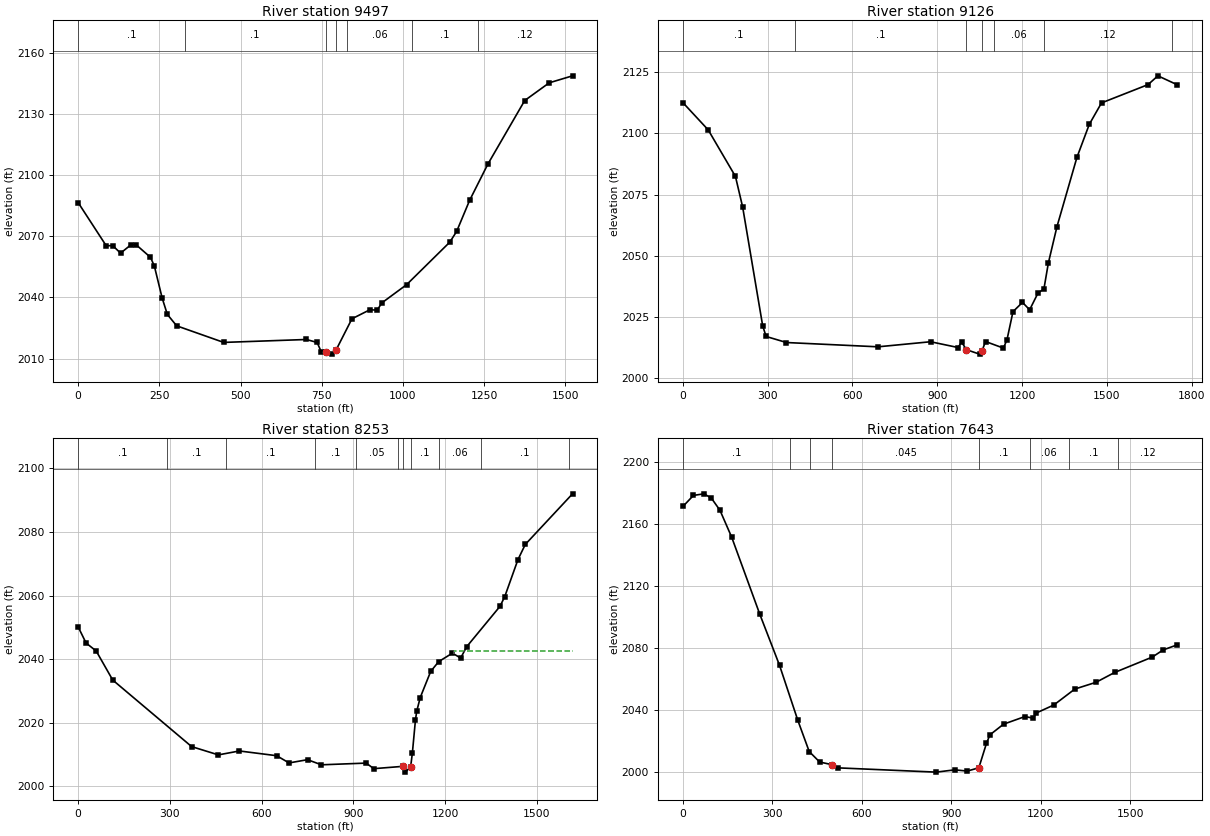
Type RM Length L Ch R = 1 ,9497    ,370.4,370.3,369.5
XS GIS Cut Line= 4
2449972.35578517535268.3700084172450258.28116117535282.464921319
2451085.85390439535046.8785199652451424.13181403534883.780242104
#Sta/Elev= 30
       0 2086.52    86.5 2065.34   106.5 2065.43   130.6 2061.73   162.6 2065.82
   178.6 2065.83   222.7  2059.7   234.7  2055.4   258.7 2039.74   274.7 2031.69
   303.4 2026.12   448.2 2017.99   702.6 2019.42   735.9 2017.97   748.4 2013.44
   762.2 2013.32   781.8 2012.25   794.1 2014.23   843.1 2029.57   898.1 2033.97
   920.8 2033.83   935.5  2037.4  1011.5  2046.3  1144.2 2067.09  1165.4 2072.35
  1205.4 2087.59  1261.2 2105.24  1375.1 2136.52  1450.6  2145.2  1522.3 2148.62
#Mann= 7 ,-1 , 0
       0      .1       0   327.7      .1       0   762.2    .045       0
   794.1      .1       0  827.68     .06       0 1027.67      .1       0
 1230.58     .12       0
Bank Sta=762.2,794.1
XS Rating Curve= 0 ,0
Exp/Cntr(USF)=0,0
Exp/Cntr=0.3,0.1

Type RM Length L Ch R = 1 ,9126    ,849.7,872.9,892.5
XS GIS Cut Line= 4
2449865.63715892535693.2309544482450425.40655701535640.878420814
2451188.54541268535381.1293116292451506.68773245535171.719177092
#Sta/Elev= 30
       0  2112.6    89.5 2101.46   185.9 2082.44   211.4 2069.94   282.3 2021.37
   294.4 2017.04   366.5 2014.56   690.4 2012.81   876.3 2014.88   973.5 2012.52
   986.2 2014.77    1003 2011.64  1049.5 2009.82    1058 2011.07  1070.7 2014.98
    1134 2012.28  1146.7 2015.71  1167.9 2027.18  1201.5 2030.96  1226.8 2027.94
  1256.6 2034.83  1277.3 2036.43    1293 2047.04  1323.4 2061.88  1394.2 2090.25
  1437.9 2103.74  1481.1 2112.48  1645.9 2119.97  1680.6 2123.55  1749.2 2119.89
#Mann= 7 ,-1 , 0
       0      .1       0  396.06      .1       0    1003    .045       0
    1058      .1       0 1099.16     .06       0 1279.16     .12       0
 1730.51      .1       0
Bank Sta=1003,1058
XS Rating Curve= 0 ,0
Exp/Cntr(USF)=0,0
Exp/Cntr=0.3,0.1

Type RM Length L Ch R = 1 ,8253    ,790.6,610.8,602.3
XS GIS Cut Line= 4
2449913.96257458535783.8411088152450427.42011599535930.830914788
2451023.43357583536387.908804595 2451299.2911569536571.142672314
#Sta/Elev= 30
       0 2050.16    25.8  2045.1    59.1 2042.56   113.1 2033.44   371.1 2012.52
   458.5 2009.92   527.2 2011.15   649.2 2009.66   689.5 2007.39     750 2008.41
   795.4  2006.8   941.7 2007.34   966.7 2005.59  1061.4 2006.31    1070  2004.5
  1087.1 2006.16  1092.8 2010.54  1102.8 2020.85  1107.1 2023.68  1118.5 2027.95
  1152.7 2036.15  1178.8 2039.23  1223.8  2041.9  1250.6 2040.35  1270.4 2043.92
  1379.2  2056.6  1394.8 2059.66    1438  2071.3    1462 2076.07  1616.4 2091.97
#Mann= 11 ,-1 , 0
       0      .1       0  290.23      .1       0  484.42      .1       0
  775.01      .1       0  909.88     .05       0 1044.75    .055       0
  1061.4    .045       0  1087.1      .1       0 1179.61     .06       0
 1316.59      .1       0 1605.73     .12       0
#XS Ineff= 1 ,-1
 1230.191616.351 2042.59
Permanent Ineff=
       F
Bank Sta=1061.4,1087.1
XS Rating Curve= 0 ,0
Exp/Cntr(USF)=0,0
Exp/Cntr=0.3,0.1

Type RM Length L Ch R = 1 ,7643    ,447.6,356.9,339.9
XS GIS Cut Line= 4
2449662.26770134536017.4139511832450042.83034968536299.312209214
2450632.80313256536861.0951662882450961.01324727537032.247680092
#Sta/Elev= 30
       0 2171.21    35.4 2178.35    70.3 2179.37    95.2 2176.69   124.4 2168.74
   163.8 2151.35   257.8 2101.82   324.2 2068.79   385.5 2033.34   423.7 2013.21
   458.9 2006.44   501.1 2004.72   521.3 2002.68     850 1999.94   911.8 2001.41
     954 2000.62   992.7 2002.73  1018.2 2018.42  1029.8 2023.96  1075.5 2030.85
  1147.3 2035.77  1174.9 2034.75    1186 2038.11  1244.5 2043.25  1314.7  2053.5
  1385.9 2057.86  1448.3  2064.2  1574.7 2074.13  1610.7  2078.7  1658.4 2082.02
#Mann= 8 ,-1 , 0
       0      .1       0  358.95      .1       0  426.73      .1       0
   501.1    .045       0   992.7      .1       0 1162.75     .06       0
 1294.43      .1       0  1458.9     .12       0
Bank Sta=501.1,992.7
XS Rating Curve= 0 ,0
Exp/Cntr(USF)=0,0
Exp/Cntr=0.3,0.1