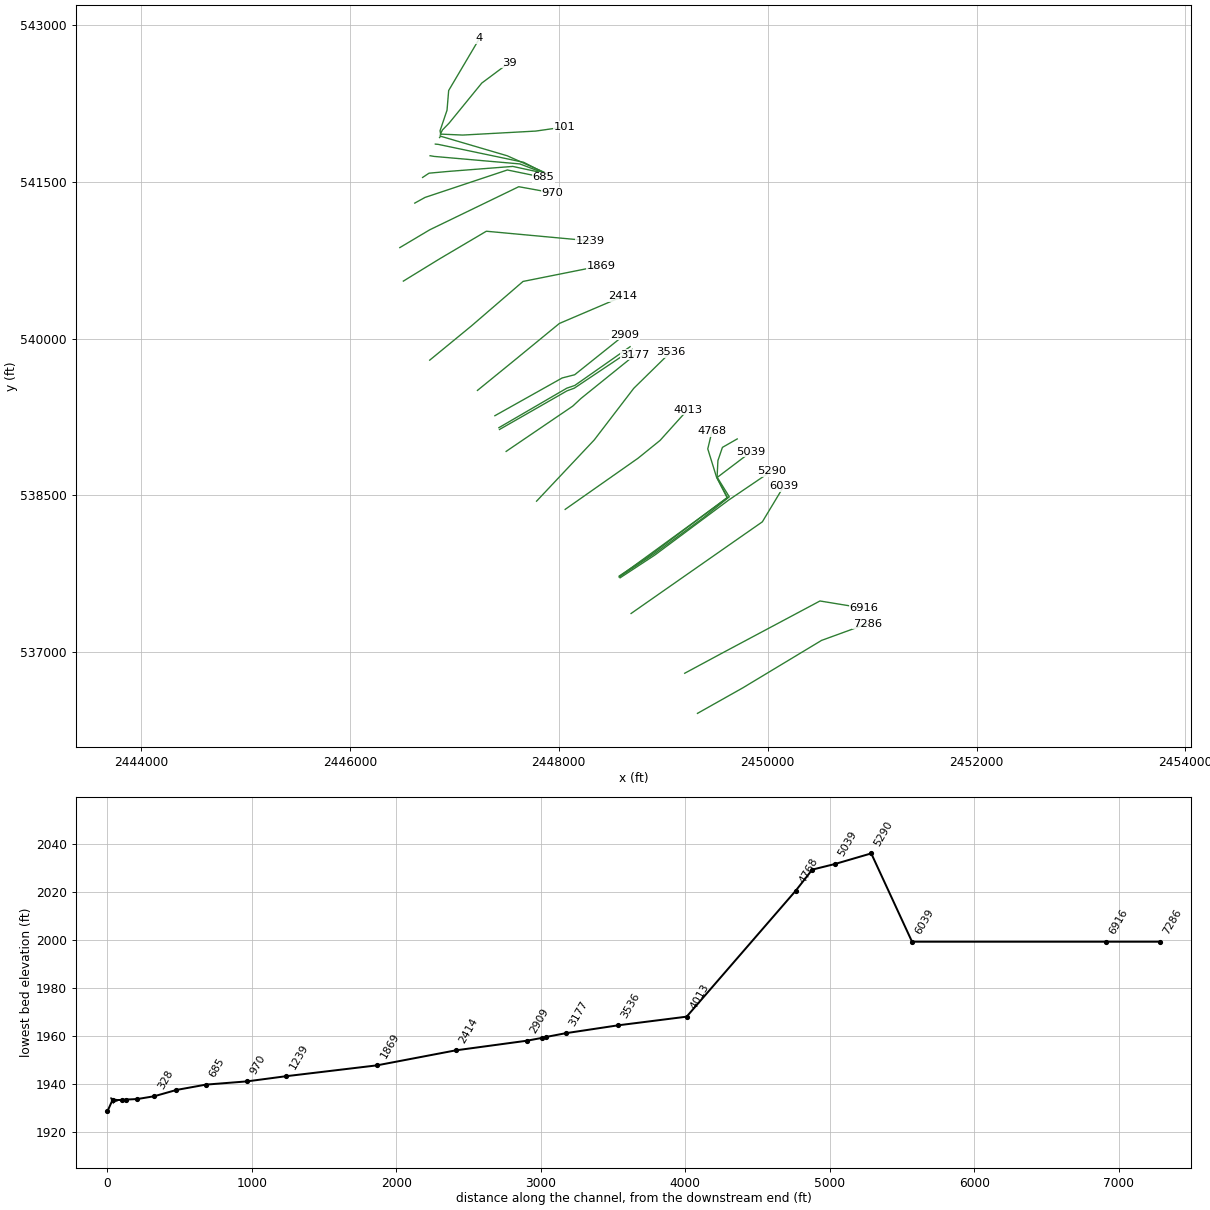
HEC-RAS study BRUSHFK.prj: BRUSHFK

--- BRUSHFK.g01 (geometry) --- (continued)

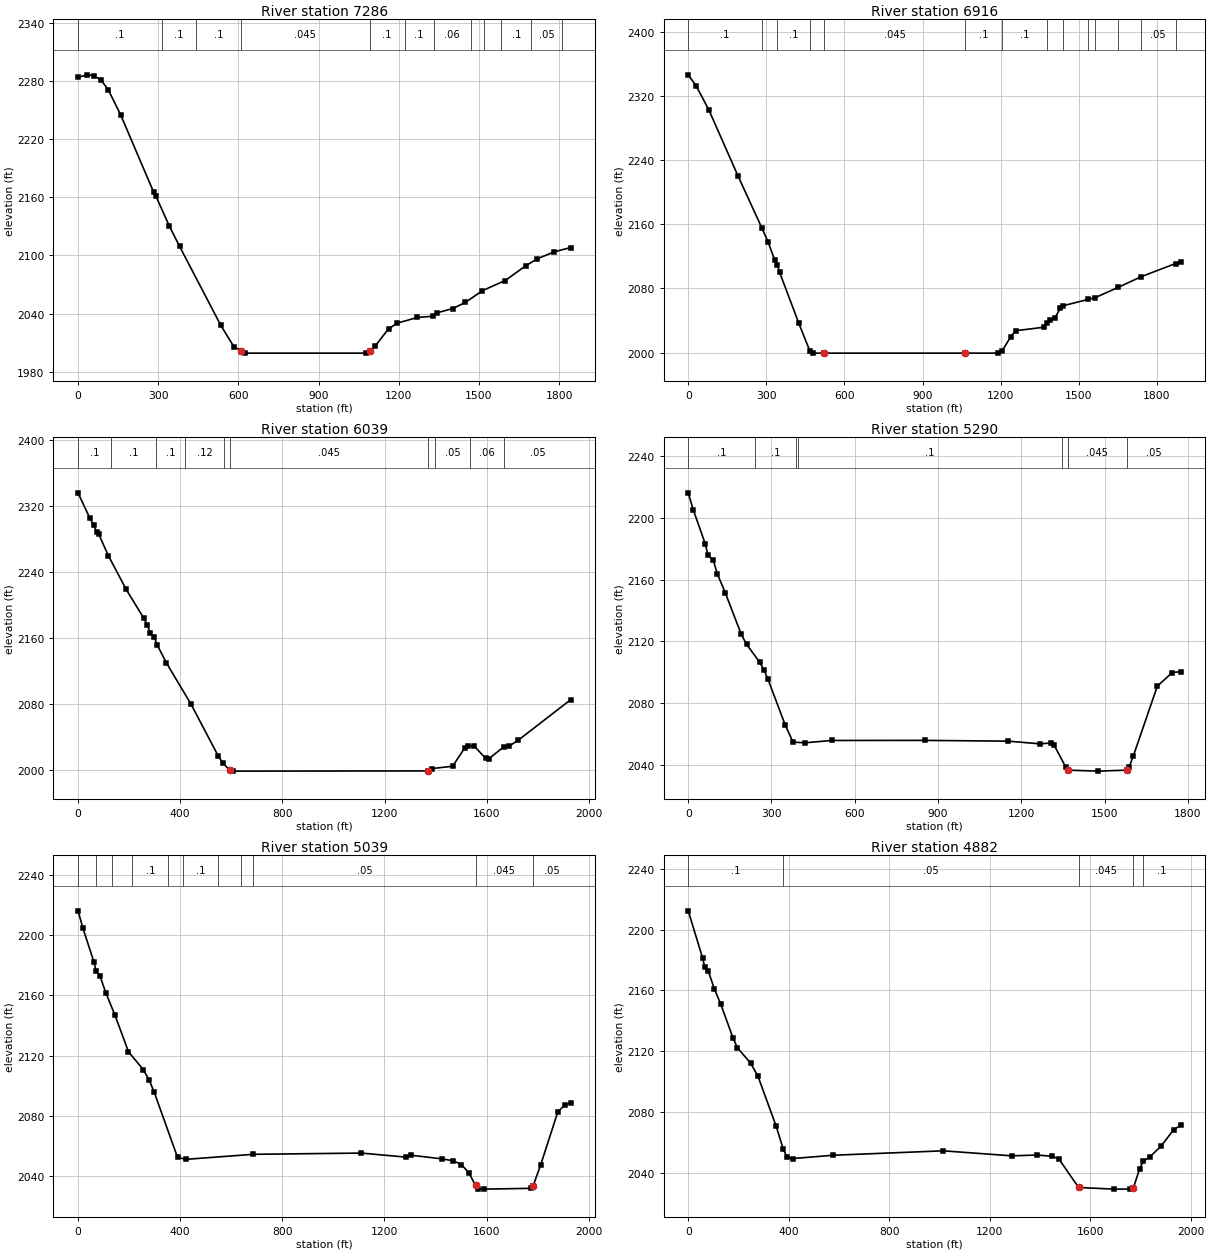
Type RM Length L Ch R = 1 ,7286    ,381.9,369.2,360.8
XS GIS Cut Line= 4
2449328.01690968536412.0715124262449760.93209165536655.712149723
2450516.01671137537110.7764805442450952.95901132537269.847640432
#Sta/Elev= 30
       0 2283.58    33.4 2286.14    58.2 2285.44    86.3 2280.64   113.3 2270.64
   159.7 2244.74     283 2165.13   291.2 2161.19   341.8 2130.13     380 2109.26
   533.9 2028.04   582.9 2005.92   608.2  2001.9     625 1999.22    1078 1999.22
  1091.9 2001.84  1112.4 2006.61  1161.9  2024.3  1194.8 2030.13  1269.5 2035.96
  1330.2 2037.34  1344.2 2040.86  1402.6  2045.2  1449.7 2051.55  1513.2 2063.58
  1598.4 2074.05    1675 2089.19  1717.6 2096.34  1781.4 2103.59  1843.4 2108.06
#Mann= 12 ,-1 , 0
       0      .1       0  315.15      .1       0   442.2      .1       0
   608.2    .045       0  1091.9      .1       0 1222.04      .1       0
 1331.47     .06       0 1469.32      .1       0 1518.21     .05       0
 1583.11      .1       0 1696.91     .05       0  1810.7      .1       0
Bank Sta=608.2,1091.9
XS Rating Curve= 0 ,0
Exp/Cntr(USF)=0,0
Exp/Cntr=0.3,0.1

Type RM Length L Ch R = 1 ,6916    ,953,1343.8,1259.3
XS GIS Cut Line= 4
2449205.93962322536796.2831045872449562.20640953536988.119066446
2450500.83236577537488.2628241512450918.76071125 537419.74998063
#Sta/Elev= 30
       0 2346.17    30.8  2332.2    79.3 2302.42   191.1 2220.25   283.1 2155.09
   306.7 2137.97   332.6 2114.74   342.1 2109.04   350.7 2100.19   424.8 2036.43
   467.1 2001.94   477.8 1999.22   519.9 1999.22  1064.9 1999.22  1190.6 1999.23
  1205.4 2001.99  1239.2 2019.94  1257.3 2027.14  1366.1 2031.52  1379.1 2036.55
  1388.8 2040.48  1406.9 2042.44  1429.6 2055.46  1438.6 2058.23    1535 2066.09
  1563.4 2068.44  1652.1 2081.33  1739.2 2094.44  1871.4 2110.89  1891.7  2112.6
#Mann= 14 ,-1 , 0
       0      .1       0   283.1      .1       0   342.1      .1       0
   467.1      .1       0   519.9    .045       0  1064.9      .1       0
  1205.4      .1       0  1379.1      .1       0  1438.6     .06       0
    1535      .1       0  1563.4     .05       0  1652.1      .1       0
  1739.2     .05       0  1871.4      .1       0
Bank Sta=519.9,1064.9
XS Rating Curve= 0 ,0
Exp/Cntr(USF)=0,0
Exp/Cntr=0.5,0.3

Type RM Length L Ch R = 1 ,6039    ,481.5,282.4,285.8
XS GIS Cut Line= 4
2448692.23581813537368.5303993192449712.03091975538080.772259639
2449949.03232401 538245.938569182450153.12863635538584.701658245
#Sta/Elev= 30
       0 2335.71      46 2305.15    61.6 2296.68    72.4 2288.05    81.1 2285.68
   118.4  2259.9   188.5 2218.88   256.8 2184.37   270.7 2176.27   283.6 2165.78
   297.5 2161.72   310.4  2151.5   345.3 2130.38   442.2 2080.21   549.5 2017.11
   566.5 2009.25   593.62000.293   604.9 1999.22  1370.9 1999.48  1383.7 2002.23
  1466.6 2005.16  1513.4 2027.16  1525.1  2030.1  1551.6 2029.26  1595.9 2014.55
  1607.6 2013.99  1665.8 2028.41    1688 2029.63  1722.1  2036.3  1928.3 2085.56
#Mann= 10 ,-1 , 0
       0      .1       0  129.02      .1       0  303.71      .1       0
  420.18     .12       0  572.16      .1       0   593.6    .045       0
  1370.9      .1       0 1397.99     .05       0 1535.66     .06       0
 1667.65     .05       0
Bank Sta=593.6,1370.9
XS Rating Curve= 0 ,0
Exp/Cntr(USF)=0,0
Exp/Cntr=0.5,0.3

Type RM Length L Ch R = 1 ,5290    ,9.8,250.8,298.4
XS GIS Cut Line= 4
2448587.02720285537709.9221432462448918.14579165537926.939056174
2449627.36601225538454.9389680412450036.78967272538732.362650547
#Sta/Elev= 30
       0 2216.12    17.8 2205.32    61.2 2183.22    71.4  2175.7    90.1 2172.73
   104.5 2163.79   133.6 2151.43     191 2124.58   210.1 2118.11   257.2 2106.54
   272.3 2101.65   286.4 2095.92   350.1 2065.57   377.5 2054.81   419.2 2054.32
   516.4 2055.84   851.3  2055.9  1152.7 2055.39  1268.2 2053.66  1308.5 2054.25
    1317 2053.21  1360.2 2038.62  1369.22036.621  1477.4    2036  1579.12036.627
  1588.6  2038.7  1603.1 2045.57    1690 2090.94  1743.3 2099.75  1774.6 2100.42
#Mann= 8 ,-1 , 0
       0      .1       0  241.11      .1       0  386.66     .12       0
  395.31      .1       0 1347.45     .05       0 1369.18     .05       0
  1369.2    .045       0  1579.1     .05       0
Bank Sta=1369.2,1579.1
XS Rating Curve= 0 ,0
Exp/Cntr(USF)=0,0
Exp/Cntr=0.5,0.3

Type RM Length L Ch R = 1 ,5039    ,7.5,157.5,86.7
XS GIS Cut Line= 6
2448578.34137869537716.811106177 2448912.5099796537939.136762212
2449382.39765449538283.677740758 2449632.7386476538485.635372106
2449517.54367452538671.5254337942449839.90834965538915.820247043
#Sta/Elev= 30
       0 2215.97    19.1 2204.44    62.4 2182.05      71 2175.88    85.5 2173.06
   108.5 2161.79   144.6 2146.88   197.5  2122.6   255.7 2110.75   279.1 2103.64
   298.4 2095.77   389.6 2052.67   422.8 2051.33   686.9 2054.66  1110.2 2055.47
  1285.2 2052.78  1305.7 2054.03  1424.2 2051.67  1469.6 2050.36  1501.4 2047.89
    1531  2042.4  1556.9 2034.02  1566.5 2031.73  1590.1 2031.59  1773.7 2032.12
  1782.1 2033.55  1812.5 2047.84  1879.3 2082.83  1907.8 2087.44  1929.4 2088.75
#Mann= 11 ,-1 , 0
       0      .1       0   71.23      .1       0  134.52      .1       0
  212.68      .1       0  354.14     .12       0  410.26      .1       0
  548.13     .12       0  637.06      .1       0   686.9     .05       0
  1556.9    .045       0  1782.1     .05       0
Bank Sta=1556.9,1782.1
XS Rating Curve= 0 ,0
Exp/Cntr(USF)=0,0
Exp/Cntr=0.5,0.3

Type RM Length L Ch R = 1 ,4882    ,4.9,114.2,27.3
XS GIS Cut Line= 6
2448580.40357476537722.2679649162449616.31184695538477.442288006
2449515.51195114538668.8694816832449523.90077357 538832.61985145
2449566.90083392538958.968013495 2449708.6967516539039.902878441
#Sta/Elev= 30
       0 2212.39    56.9 2181.56    65.8 2175.46      80 2172.67   103.9 2161.03
     129  2151.2     178 2128.88   195.2 2122.38   248.3 2112.17   277.3 2103.68
   349.7 2070.82   378.6 2055.33   393.2 2050.42   418.1 2049.39   577.1 2051.54
  1015.1 2054.45    1288 2051.15  1389.5 2051.68    1448 2050.86  1475.1 2049.13
  1553.9 2030.32  1694.8 2029.24  1759.2 2029.25  1771.8 2030.09  1797.1  2042.8
  1810.8 2047.49  1838.5 2050.59  1882.8  2057.7  1931.9  2068.3  1960.5 2071.33
#Mann= 5 ,-1 , 0
       0      .1       0   378.6     .05       0  1553.9    .045       0
  1771.8     .05       0  1810.8      .1       0
Bank Sta=1553.9,1771.8
XS Rating Curve= 0 ,0
Exp/Cntr(USF)=0,0
Exp/Cntr=0.3,0.1

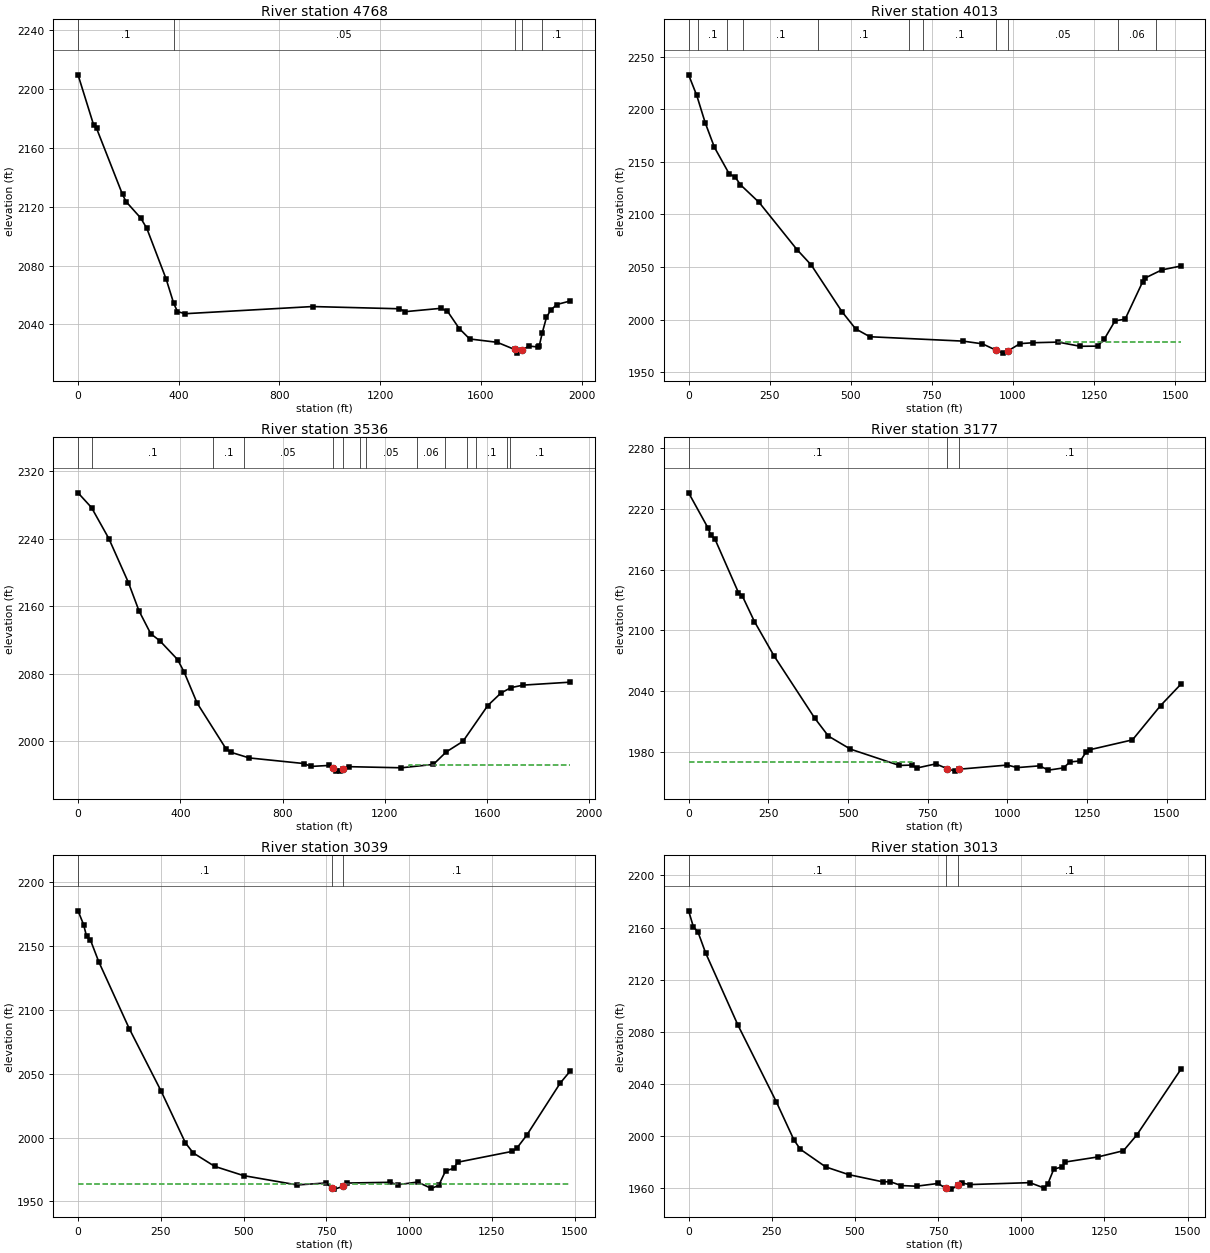
Type RM Length L Ch R = 1 ,4768    ,825.7,755.1,709.6
XS GIS Cut Line= 6
2448579.71219407537727.8365809282448859.68493427537914.485074395
2449611.56141267538477.9522244842449511.19382657538671.644057328
2449426.67375405538944.5734581522449467.24514942539114.660281412
#Sta/Elev= 30
       0 2209.57    62.1 2175.44    73.6 2173.21   176.7 2128.26   191.1 2123.35
   248.8  2112.3   272.9 2105.37   350.2 2070.73     380 2054.31   394.9 2048.72
   424.9 2047.25   931.4 2052.12  1276.1 2050.61    1300 2048.65  1440.4  2050.9
    1467 2049.04  1514.2 2037.17  1555.8 2030.09    1665 2027.82  1734.2 2022.95
  1744.8 2020.47  1762.8  2022.4  1790.8 2025.28  1828.6  2024.6  1832.2 2025.54
  1844.2 2034.43  1860.7 2044.81  1877.1 2049.62  1901.8 2053.51    1955  2055.9
#Mann= 5 ,-1 , 0
       0      .1       0     380     .05       0  1734.2    .045       0
  1762.8     .05       0  1844.2      .1       0
Bank Sta=1734.2,1762.8
XS Rating Curve= 0 ,0
Exp/Cntr(USF)=0,0
Exp/Cntr=0.3,0.1

Type RM Length L Ch R = 1 ,4013    ,465.9,476.2,485.2
XS GIS Cut Line= 4
2448061.26457875538365.4474575552448759.29836054538855.413477465
2448969.60341018539025.4473473882449233.60336611539318.532044229
#Sta/Elev= 30
       0 2232.92    25.1 2213.31    51.2 2187.26    79.6 2163.92   125.6 2138.39
   142.8 2135.89     160 2128.24   217.5 2111.43   334.1 2066.59   378.3 2051.83
     473 2007.42   514.9 1991.14   558.9  1983.6   846.3 1979.43   906.1 1976.84
   948.8 1970.68   970.4    1968   985.6 1970.27  1021.9 1977.05    1063  1977.9
  1139.3 1978.49  1207.2 1974.52  1261.1 1974.67  1281.3 1981.11  1314.9 1998.73
    1346 2000.32  1399.8 2035.71  1408.3 2039.58    1459 2047.21  1517.7 2050.92
#Mann= 11 ,-1 , 0
       0      .1       0   30.34      .1       0  118.44      .1       0
  169.06      .1       0  399.76      .1       0  681.09     .05       0
  723.92      .1       0   948.8    .045       0   985.6     .05       0
 1324.31     .06       0 1440.84      .1       0
#XS Ineff= 2 , 0
                         1136.01         1978.64
Permanent Ineff=
       F       F
Bank Sta=948.8,985.6
XS Rating Curve= 0 ,0
Exp/Cntr(USF)=0,0
Exp/Cntr=0.3,0.1

Type RM Length L Ch R = 1 ,3536    ,360.8,359.8,352.9
XS GIS Cut Line= 4
2447787.27406393538443.9032503382448339.69079532539030.419779966
2448718.19855572539524.8668543622449072.83645736539872.684796351
#Sta/Elev= 30
       0 2294.22    52.7 2276.77   120.6 2239.96     197 2187.93   238.4  2154.4
   284.3 2127.26   320.1 2118.82   389.4 2096.62   414.9 2081.84   465.8 2045.03
     579 1990.76   597.6 1986.75   669.5 1980.03   881.9 1973.41   912.1 1969.96
   982.6 1971.13   996.5 1968.35    1008  1964.5  1022.9 1964.38  1036.5 1967.34
  1058.2 1969.66  1264.7 1968.34  1389.8 1972.34  1440.4 1987.18  1505.6 1999.68
  1602.7 2042.13  1654.1 2056.92  1693.3 2063.33  1741.4 2066.33  1925.1 2069.82
#Mann= 14 ,-1 , 0
       0      .1       0   56.57      .1       0  529.68      .1       0
  647.95     .05       0   996.5    .045       0  1036.5     .05       0
 1101.89      .1       0  1125.6     .05       0 1324.06     .06       0
 1435.79      .1       0 1521.94     .12       0 1557.47      .1       0
 1679.15     .12       0 1689.52      .1       0
#XS Ineff= 2 , 0
                         1295.28         1971.67
Permanent Ineff=
       F       F
Bank Sta=996.5,1036.5
XS Rating Curve= 0 ,0
Exp/Cntr(USF)=0,0
Exp/Cntr=0.3,0.1

Type RM Length L Ch R = 1 ,3177    ,144.7,137.7,126.3
XS GIS Cut Line= 4
2447495.94621318538920.5690741642448133.58243244539353.887451129
2448213.11555226539427.9355282052448730.08083111 539844.79877693
#Sta/Elev= 30
       0 2235.77    61.1 2200.93    69.9 2193.73    82.4 2190.29   156.3 2137.29
   167.8 2134.44   206.5 2108.72   267.4 2075.13   395.5 2013.42   438.5 1995.69
   507.6 1982.81   661.1 1966.72   700.5  1967.1   715.8 1964.19   775.3 1968.27
   811.41963.499   834.7 1961.12   847.61962.989   999.9 1967.11  1030.7  1964.6
    1101 1966.35  1128.3 1962.09  1175.9 1964.29  1195.8 1970.17  1228.4 1971.16
  1247.5 1980.34  1260.3 1982.39  1392.1 1991.97  1480.2  2025.8  1543.7 2046.81
#Mann= 3 , 0 , 0
       0      .1       0   811.4    .045       0   847.6      .1       0
#XS Ineff= 2 , 0
           699.8    1970
Permanent Ineff=
       F       F
Bank Sta=811.4,847.6
XS Rating Curve= 0 ,0
Exp/Cntr(USF)=0,0
Exp/Cntr=0.5,0.3

Type RM Length L Ch R = 1 ,3039    ,25.2,25.9,24.7
XS GIS Cut Line= 4
2447432.47158444539130.2875581182448079.40788566 539500.65835039
 2448148.2337221539525.7595377982448703.69870796539897.419054576
#Sta/Elev= 30
       0  2177.7    16.8  2166.9    25.6 2157.93    37.3 2154.95    62.5 2137.87
   154.7  2085.4   251.3 2036.24   324.5 1995.78     348 1987.92   412.8 1977.39
   500.4 1970.12   662.2 1962.82     749 1964.35   766.81960.523   774.6 1959.54
   801.31961.674   812.2  1964.3   942.4 1964.89   966.1 1962.99  1026.1 1965.09
  1067.2  1960.1  1089.5 1962.39  1110.5 1973.84  1134.6  1975.8  1147.2 1980.65
  1312.6 1989.18  1325.9  1991.7    1356 2001.96    1457 2042.74    1487  2052.1
#Mann= 3 , 0 , 0
       0      .1       0   766.8    .045       0   801.3      .1       0
#XS Ineff= 2 , 0
          761.52 1963.58  806.81         1963.35
Permanent Ineff=
       F       F
Bank Sta=766.8,801.3
XS Rating Curve= 0 ,0
Exp/Cntr(USF)=0,0
Exp/Cntr=0.5,0.3

Type RM Length L Ch R = 1 ,3013    ,105.4,104.1,101.4
XS GIS Cut Line= 4
2447426.56042243539147.4990051892448077.44301993539526.254919434
2448152.97205855539551.8015060252448682.78605003539922.782372176
#Sta/Elev= 30
       0 2172.83    14.3 2160.58      28  2156.7    51.1 2140.53   148.3 2085.09
     264 2026.04   316.9  1996.8   336.1 1989.74   412.2 1976.22   481.5  1970.3
   583.3  1964.8   606.5 1964.87   638.9 1961.92   685.2 1961.43   749.9 1963.54
   773.81959.724   789.3 1959.18   809.81962.156   820.9 1963.94   844.9 1962.67
  1025.8 1964.16  1068.3 1960.09  1080.4 1963.49  1097.6 1974.49  1123.1 1976.31
  1132.8 1980.02  1230.5 1983.89  1307.3 1988.68  1347.3 2000.75  1479.6 2051.06
#Mann= 3 , 0 , 0
       0      .1       0   773.8    .045       0   809.8      .1       0
Bank Sta=773.8,809.8
XS Rating Curve= 0 ,0
Exp/Cntr(USF)=0,0
Exp/Cntr=0.5,0.3

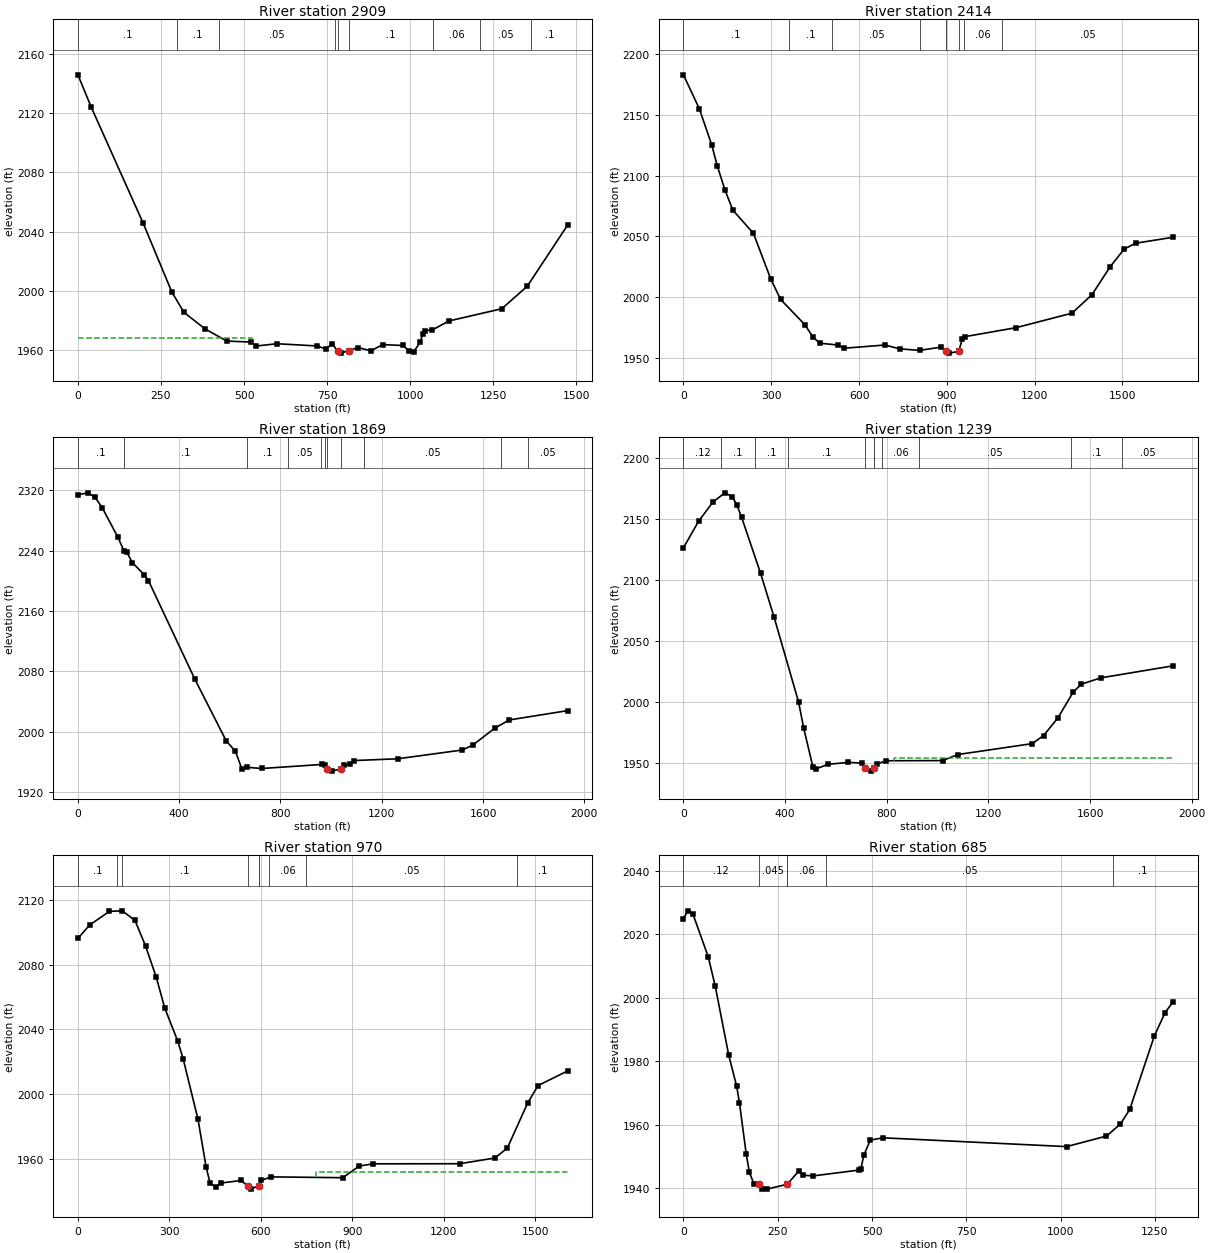
Type RM Length L Ch R = 1 ,2909    ,477.8,494.5,499.3
XS GIS Cut Line= 4
2447388.30642459539262.2984079592448032.79261121539623.756269241
2448152.14190503539654.4460876522448629.53908031540036.363827875
#Sta/Elev= 30
       0 2145.86    40.4 2123.88   196.2 2045.83   282.6 1999.26   319.2 1985.52
   381.3 1974.56   447.7 1966.15   519.4 1965.47   537.4 1962.82     599 1964.34
   719.2 1962.84   746.4 1960.82   765.7 1964.36   781.8 1959.11   790.5    1958
   815.1 1959.61   841.7 1961.78   882.1 1959.58   916.7 1963.73   978.2 1963.16
   997.3 1959.27  1010.1 1958.82  1029.4 1965.21  1037.9 1970.87  1044.8 1973.19
  1066.4 1973.63  1116.5 1979.71  1275.3 1987.95  1352.1 2003.12  1473.5 2044.39
#Mann= 9 ,-1 , 0
       0      .1       0  298.54      .1       0  425.44     .05       0
  772.87      .1       0   781.8    .045       0   815.1      .1       0
 1068.39     .06       0 1211.25     .05       0  1364.5      .1       0
#XS Ineff= 2 , 0
          524.59 1968.09
Permanent Ineff=
       F       F
Bank Sta=781.8,815.1
XS Rating Curve= 0 ,0
Exp/Cntr(USF)=0,0
Exp/Cntr=0.3,0.1

Type RM Length L Ch R = 1 ,2414    ,538,545.4,538.7
XS GIS Cut Line= 4
2447221.21741324539504.4069754212447569.03535523539787.435300765
2448005.51277263540145.483182224 2448612.4891812540404.641648804
#Sta/Elev= 30
       0 2182.82    54.6 2154.74    96.7 2125.08   115.4 2108.03   142.2 2087.88
   168.7 2071.57   239.2 2052.44   297.9 2015.13     332 1998.12   414.5 1977.44
   443.6 1966.84   466.3 1962.13   528.2 1960.61   548.7    1958   688.6 1960.64
   739.2 1957.46   807.1 1956.25   878.4 1958.85   898.41955.374     908 1953.97
   940.21955.395   952.3 1965.18   960.8 1967.49  1136.1 1974.88  1327.5 1986.85
    1396 2002.11  1457.9 2025.03  1505.8 2039.52  1544.9 2044.35    1673 2049.25
#Mann= 9 ,-1 , 0
       0      .1       0  359.16      .1       0  508.86     .05       0
  809.07      .1       0  898.36      .1       0   898.4    .045       0
   940.2      .1       0  959.17     .06       0 1088.38     .05       0
Bank Sta=898.4,940.2
XS Rating Curve= 0 ,0
Exp/Cntr(USF)=0,0
Exp/Cntr=0.3,0.1

Type RM Length L Ch R = 1 ,1869    ,633.4,630.2,625
XS GIS Cut Line= 4
 2446764.2801169539794.2552604122447163.24775624 540121.61332346
2447657.69483064540547.8608013882448407.89039179540697.899913618
#Sta/Elev= 30
       0 2313.93    39.2 2316.45    67.6 2310.62      96 2296.74   158.5  2257.3
   181.3 2239.99   192.6 2237.95   215.3 2223.91   261.9 2207.99   278.5 2200.24
   461.3 2069.89   585.4 1988.05   622.2 1973.87   647.4 1950.74   666.9 1952.77
   726.3 1951.21   965.2 1956.59   974.9 1955.58   985.4 1950.53  1001.6 1947.72
  1037.41950.343  1049.8 1955.79  1075.4 1956.68  1089.5 1961.72  1263.3 1964.08
  1518.2 1975.72  1559.9 1982.25  1648.3 2005.14  1704.3 2015.59  1933.9 2027.84
#Mann= 11 ,-1 , 0
       0      .1       0  183.97      .1       0  666.54      .1       0
  831.34     .05       0  959.42      .1       0   975.4     .06       0
   985.4    .045       0  1037.4     .06       0 1129.83     .05       0
  1672.3      .1       0 1778.35     .05       0
Bank Sta=985.4,1037.4
XS Rating Curve= 0 ,0
Exp/Cntr(USF)=0,0
Exp/Cntr=0.3,0.1

Type RM Length L Ch R = 1 ,1239    ,270.5,268.3,266.7
XS GIS Cut Line= 4
2446511.94160997540551.2707812112446856.34957214540762.689530263
2447306.46690883 541028.667956492448302.18101726540936.598501258
#Sta/Elev= 30
       0 2126.16    59.9    2148   115.9  2163.6   162.9 2171.19     192 2168.07
   209.8 2161.39   228.6 2151.35   303.7 2105.12   356.6 2069.38   453.4 1999.51
   473.2 1978.35   509.1 1946.94   523.1 1945.18   569.5 1948.78   648.3 1950.35
     701 1949.81   713.6 1945.36   736.8 1943.19     7481945.437   762.3 1949.08
   797.2 1951.68  1019.6 1951.83  1079.9 1956.79  1372.4 1965.72  1417.3 1972.36
  1473.6 1986.86  1533.8 2008.01  1565.9 2014.44  1642.4  2019.6  1926.9 2029.47
#Mann= 11 ,-1 , 0
       0     .12       0  149.47      .1       0  280.58      .1       0
  411.58      .1       0   713.6    .045       0     748      .1       0
  748.02      .1       0  780.33     .06       0  928.21     .05       0
 1525.52      .1       0 1724.63     .05       0
#XS Ineff= 2 , 0
                          828.53         1953.69
Permanent Ineff=
       F       F
Bank Sta=713.6,748
XS Rating Curve= 0 ,0
Exp/Cntr(USF)=0,0
Exp/Cntr=0.3,0.1

Type RM Length L Ch R = 1 ,970     ,293.4,285.9,278.3
XS GIS Cut Line= 4
2446477.84181174540871.808884613 2446764.2801169541042.307875784
2447616.77507276541454.9154344182447937.31317616541396.945777419
#Sta/Elev= 30
       0 2096.44    38.3 2104.71   103.5 2113.22   145.4 2113.54   187.3 2107.56
   221.8 2091.83   257.1 2072.32     285 2053.21   327.3 2032.89     345 2021.99
   393.9 1984.33   420.5 1954.88   433.8 1944.59   451.6 1942.41   470.4 1944.86
   536.1 1946.43   557.2 1942.87   567.2 1941.05   592.51943.077   602.1 1946.57
   633.8 1948.64   868.7 1948.13   922.7 1955.36   968.2 1956.73  1251.9 1956.79
  1367.8 1960.34  1408.5 1966.48  1474.9 1994.28  1509.3 2005.23  1606.2  2014.3
#Mann= 9 ,-1 , 0
       0      .1       0  129.02     .12       0  143.69      .1       0
   557.2    .045       0   592.5      .1       0  592.53      .1       0
   627.3     .06       0   748.6     .05       0 1440.92      .1       0
#XS Ineff= 1 ,-1
  780.251606.177 1951.62
Permanent Ineff=
       F
Bank Sta=557.2,592.5
XS Rating Curve= 0 ,0
Exp/Cntr(USF)=0,0
Exp/Cntr=0.3,0.1

Type RM Length L Ch R = 1 ,685     ,213.3,203.7,192
XS GIS Cut Line= 4
2446621.06096432 541298.05636254 2446719.9503792541352.616039715
2447507.65571841541615.184486118 2447855.4736604541543.574909827
#Sta/Elev= 30
       0 2024.75    11.1 2027.33    24.8 2026.44    65.9 2012.79    84.2 2003.65
   120.1 1981.84   141.2 1972.03   148.6 1966.77   166.5  1950.7   174.9 1944.95
   186.5 1941.45   199.51941.244   208.7 1939.78   221.3 1939.69   275.6 1941.24
   305.6 1945.39   318.3 1944.07   343.6 1943.85   465.8 1945.69   470.1 1945.98
   478.5  1950.4   495.4 1955.13   529.1 1955.85  1015.8 1953.08  1121.7  1956.4
  1158.8  1960.2  1183.3 1964.78  1248.6 1987.94  1277.2  1995.3  1298.4 1998.73
#Mann= 6 ,-1 , 0
       0     .12       0   199.5    .045       0   275.6     .06       0
  275.63     .06       0     378     .05       0 1137.93      .1       0
Bank Sta=199.5,275.6
XS Rating Curve= 0 ,0
Exp/Cntr(USF)=0,0
Exp/Cntr=0.3,0.1

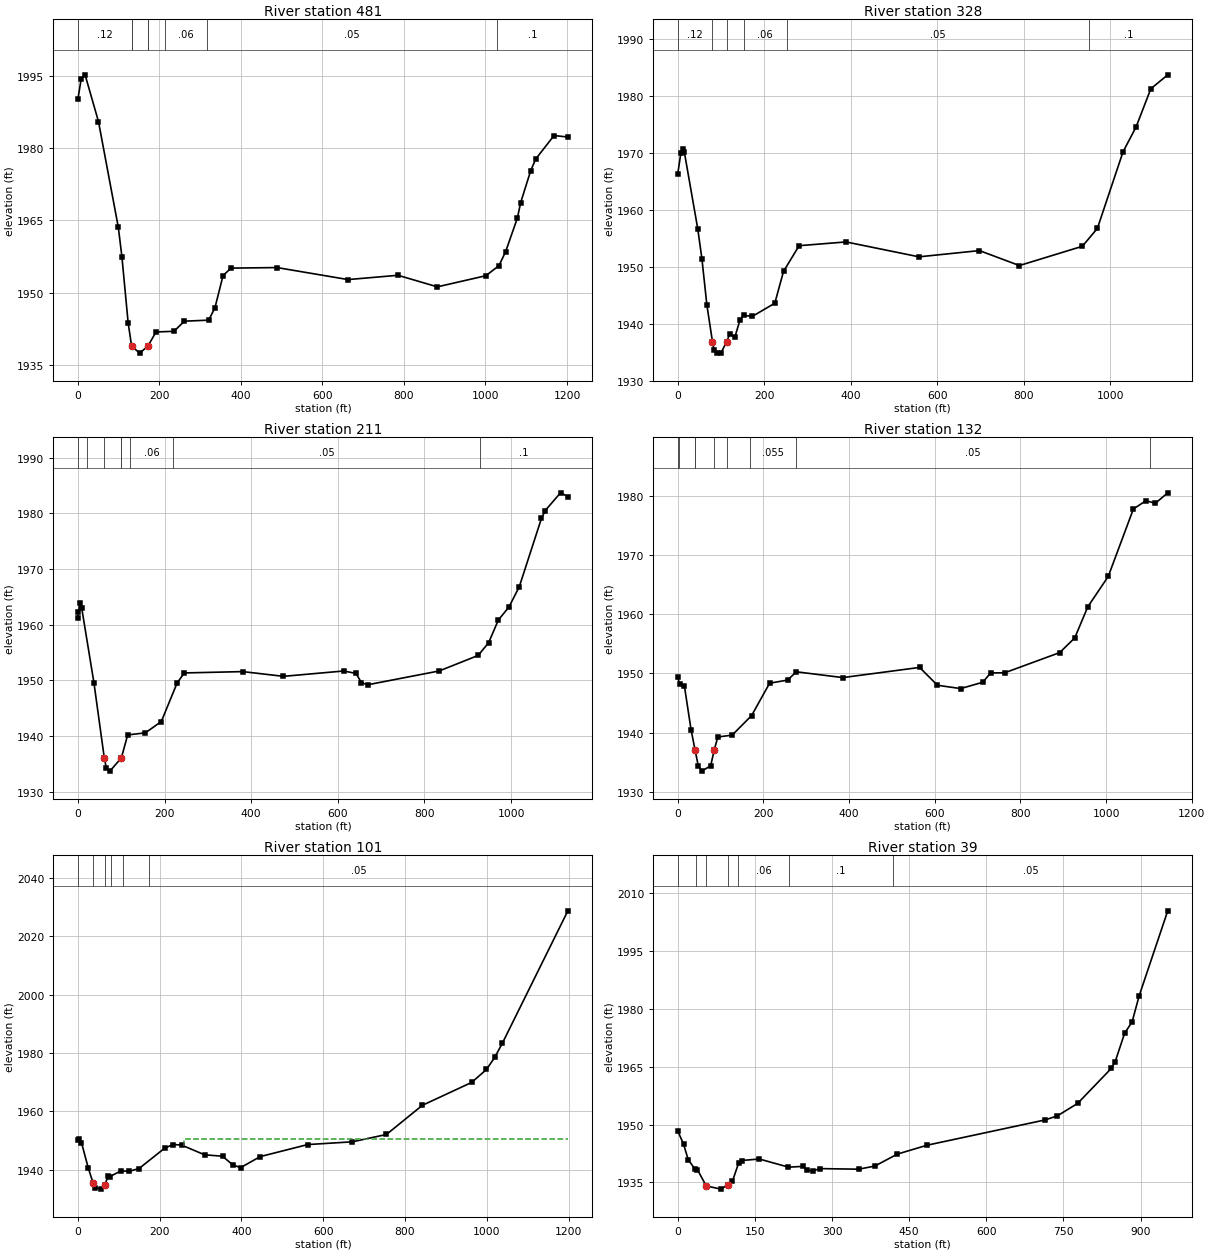
Type RM Length L Ch R = 1 ,481     ,156.6,153.1,147.7
XS GIS Cut Line= 5
2446696.08052044541543.5749098272446757.46015726541584.494667708
2446945.00904754541601.5445668252447558.80541576541649.284284353
2447875.93353934541581.084687884
#Sta/Elev= 30
       0 1990.17       8 1994.36    17.6 1995.21    50.5  1985.5    99.2 1963.54
   107.9  1957.5   123.3 1943.71   131.81938.926   151.4 1937.47   171.81938.923
   191.5 1941.86   235.7    1942   261.2  1944.1   320.8 1944.31   336.1 1946.85
   356.1 1953.56   375.6 1955.11   488.5 1955.22   662.8 1952.73   785.4 1953.62
   881.8 1951.22  1000.9 1953.53  1033.2 1955.63  1049.5 1958.55  1078.2 1965.48
  1086.3  1968.7  1110.9 1975.32  1123.2 1977.74  1168.2 1982.62  1202.1  1982.3
#Mann= 8 ,-1 , 0
       0     .12       0  131.79     .12       0   131.8    .045       0
   171.8     .12       0  171.83     .12       0  213.74     .06       0
   316.1     .05       0 1027.41      .1       0
Bank Sta=131.8,171.8
XS Rating Curve= 0 ,0
Exp/Cntr(USF)=0,0
Exp/Cntr=0.3,0.1

Type RM Length L Ch R = 1 ,328     ,118.5,117.2,113.3
XS GIS Cut Line= 4
2446767.69009673541751.5836790552446808.60985461541744.763719408
2447627.00501223541673.1541431162447879.34351916541577.674708061
#Sta/Elev= 30
       0 1966.32     7.2    1970    11.2  1970.7    15.3 1970.03    46.2 1956.62
    55.7 1951.44    67.3 1943.26    80.2 1936.85    83.8  1935.4    91.8 1934.86
    99.8 1934.88   112.81936.851   119.9 1938.15     132 1937.67     144 1940.72
     152  1941.5   172.1 1941.29   224.3 1943.61   244.4 1949.18   280.5 1953.69
   388.9 1954.35   557.6 1951.74   697.4 1952.83   789.8 1950.21   935.4 1953.59
   970.1 1956.72  1029.5 1970.16  1059.5 1974.49  1093.7  1981.2  1132.8 1983.64
#Mann= 6 ,-1 , 0
       0     .12       0    80.2    .045       0   112.8     .12       0
  152.52     .06       0   252.1     .05       0  950.74      .1       0
Bank Sta=80.2,112.8
XS Rating Curve= 0 ,0
Exp/Cntr(USF)=0,0
Exp/Cntr=0.3,0.1

Type RM Length L Ch R = 1 ,211     ,79.9,78.4,75.4
XS GIS Cut Line= 4
2446817.91568955541862.9672600072446845.26031775541860.481384716
2447663.11328858541688.9559896182447901.75731654541567.148100346
#Sta/Elev= 30
       0 1961.22      .8 1962.25     4.8 1963.97     8.9 1962.93    37.1 1949.51
    60.81936.108    65.8 1934.17    73.9 1933.69   100.41936.086   114.8 1940.19
   155.7 1940.57   192.5  1942.6   229.2 1949.56   245.6 1951.33   380.5 1951.57
   474.5 1950.72   613.4 1951.68     642 1951.25   654.3 1949.59   668.6  1949.2
   834.1 1951.69   923.8 1954.47     948 1956.75   970.5 1960.83   995.2  1963.2
    1019 1966.85    1070 1979.09  1078.8 1980.51    1114 1983.69    1131 1983.02
#Mann= 8 ,-1 , 0
       0     .05       0    21.2     .12       0    60.8    .045       0
   100.4     .12       0  100.41     .12       0  120.63     .06       0
  220.06     .05       0  927.34      .1       0
Bank Sta=60.8,100.4
XS Rating Curve= 0 ,0
Exp/Cntr(USF)=0,0
Exp/Cntr=0.3,0.1

Type RM Length L Ch R = 1 ,132     ,25.4,31.3,39.1
XS GIS Cut Line= 5
2446858.62387748541925.491394596 2446867.6155339541937.992713829
2446880.06257183541935.0576434542447506.50314523  541751.1028719
2447929.10194475541562.176349763
#Sta/Elev= 30
       0 1949.36       4 1948.25    15.4  1947.9      31 1940.47    40.2 1937.09
    47.7  1934.4      56 1933.47    76.8 1934.38    85.21937.094    93.5 1939.25
   126.9 1939.56   172.3 1942.87   214.4 1948.35   256.2 1948.88   276.9 1950.28
   385.3  1949.3   564.6 1951.02   606.3    1948   660.5 1947.44     712 1948.51
   730.6 1950.09   763.2 1950.11   891.7 1953.53   926.8 1956.01   957.4 1961.29
    1005 1966.41  1063.8 1977.84  1093.2 1979.24  1115.1  1978.8    1144 1980.57
#Mann= 9 ,-1 , 0
       0     .05       0   1.724     .12       0  40.151     .12       0
    40.2    .045       0    85.2     .12       0 114.361     .06       0
 169.054    .055       0 276.948     .05       01102.298      .1       0
Bank Sta=40.2,85.2
XS Rating Curve= 0 ,0
Exp/Cntr(USF)=0,0
Exp/Cntr=0.3,0.1

Type RM Length L Ch R = 1 ,101     ,48.8,62.3,90.3
XS GIS Cut Line= 5
2446864.56280258541948.8918981482446876.99569846 541958.27797293
2447081.03164406541949.4706659252447779.74466642541987.635662945
2448055.70695256542027.268544465
#Sta/Elev= 30
       0 1950.08     2.7  1950.6     8.7 1949.26    25.3 1940.55    37.3 1935.32
    41.4 1933.75    57.4 1933.29    66.6 1934.83    73.4 1937.82    77.4 1937.55
   105.4 1939.56   125.4  1939.4   149.5 1940.35   212.4 1947.37   232.8  1948.6
   253.6 1948.41   309.7 1945.07   353.7 1944.58   378.5 1941.64   397.8 1940.66
   445.9 1944.45     562 1948.58     671 1949.52   754.6 1952.04   842.4 1962.04
     963  1969.9   999.3 1974.34  1019.6 1978.52  1038.2 1983.36  1198.4 2028.78
#Mann= 6 ,-1 , 0
       0     .12       0    37.3    .045       0    66.6     .12       0
  81.389     .06       0 109.415    .055       0 173.474     .05       0
#XS Ineff= 1 ,-1
  260.081198.352 1950.33
Permanent Ineff=
       F
Bank Sta=37.3,66.6
XS Rating Curve= 0 ,0
Exp/Cntr(USF)=0,0
Exp/Cntr=0.3,0.1

Type RM Length L Ch R = 1 ,39      ,27.4,34.8,73.1
XS GIS Cut Line= 5
 2446869.4243152541964.9631631162446885.72664628541997.949325581
2446948.91426084542062.6971281592447262.64951883542447.201640472
2447526.64947477 542644.08296354
#Sta/Elev= 30
       0  1948.3    11.1 1944.96    20.3 1940.91    33.4 1938.45    38.3 1938.28
    55.4  1934.1    84.1 1933.28    97.6 1934.44   106.1 1935.27   118.4 1940.05
   124.2 1940.69   158.5 1941.08   215.3 1938.97     244 1939.17   250.4 1938.21
   262.3 1938.01   277.2 1938.59   351.6 1938.44   383.2 1939.25   426.9 1942.34
   484.5 1944.64   714.8 1951.21   738.4 1952.26   777.7 1955.48   843.2 1964.55
   850.5 1966.22   869.2  1973.7   883.5 1976.54   897.3 1983.33   952.9 2005.33
#Mann= 7 ,-1 , 0
       0     .12       0  35.272     .05       0    55.4    .045       0
    97.6     .05       0 116.358     .06       0 216.835      .1       0
 418.682     .05       0
Bank Sta=55.4,97.6
XS Rating Curve= 0 ,0
Exp/Cntr(USF)=0,0
Exp/Cntr=0.3,0.1

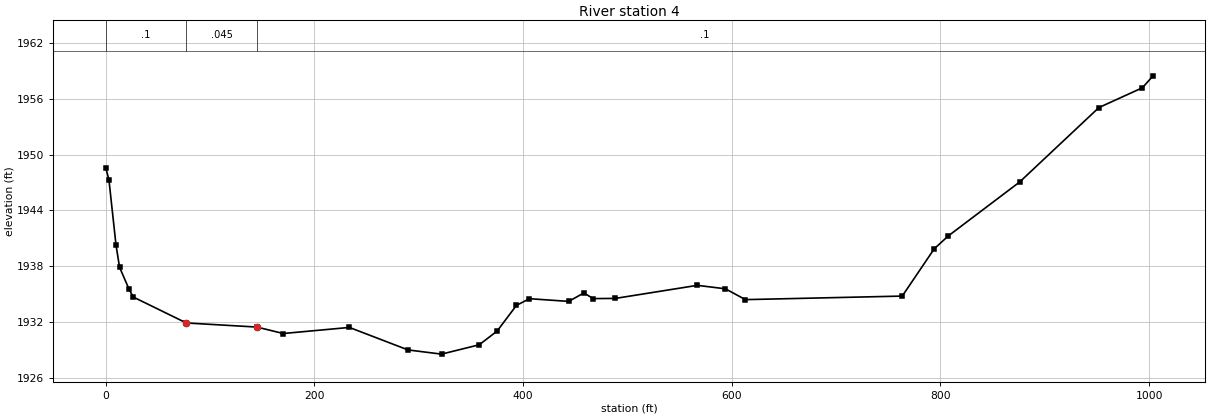
Type RM Length L Ch R = 1 ,4       ,4,4,4
XS GIS Cut Line= 5
2446868.25655088 541964.901213012446863.13475192541990.686821566
 2446930.0013267  542187.96299662446945.69042906542376.232224885
2447241.16852345542875.668649921
#Sta/Elev= 30
       0 1948.56       3 1947.31     9.8  1940.3    13.2 1937.92    22.4 1935.54
    26.3 1934.73    77.2 1931.95   144.8 1931.51   170.1 1930.82   233.5 1931.47
   289.7 1929.06   321.8 1928.61   357.9 1929.61   375.1 1931.08   393.6 1933.83
   406.1 1934.55   443.7 1934.26   458.3 1935.17   467.1 1934.56   488.4 1934.58
     567 1935.98   593.9 1935.61   613.1 1934.45   763.4 1934.83   794.1  1939.9
   807.7 1941.29   875.9 1947.05   951.9 1955.03   993.6 1957.15  1003.8 1958.43
#Mann= 3 , 0 , 0
       0      .1       0    77.2    .045       0   144.8      .1       0
Bank Sta=77.2,144.8
XS Rating Curve= 0 ,0
Exp/Cntr(USF)=0,0
Exp/Cntr=0.3,0.1
LCMann Table=0

Chan Stop Cuts=-1
Use User Specified Reach Order=0
Composite Channel Slope=5